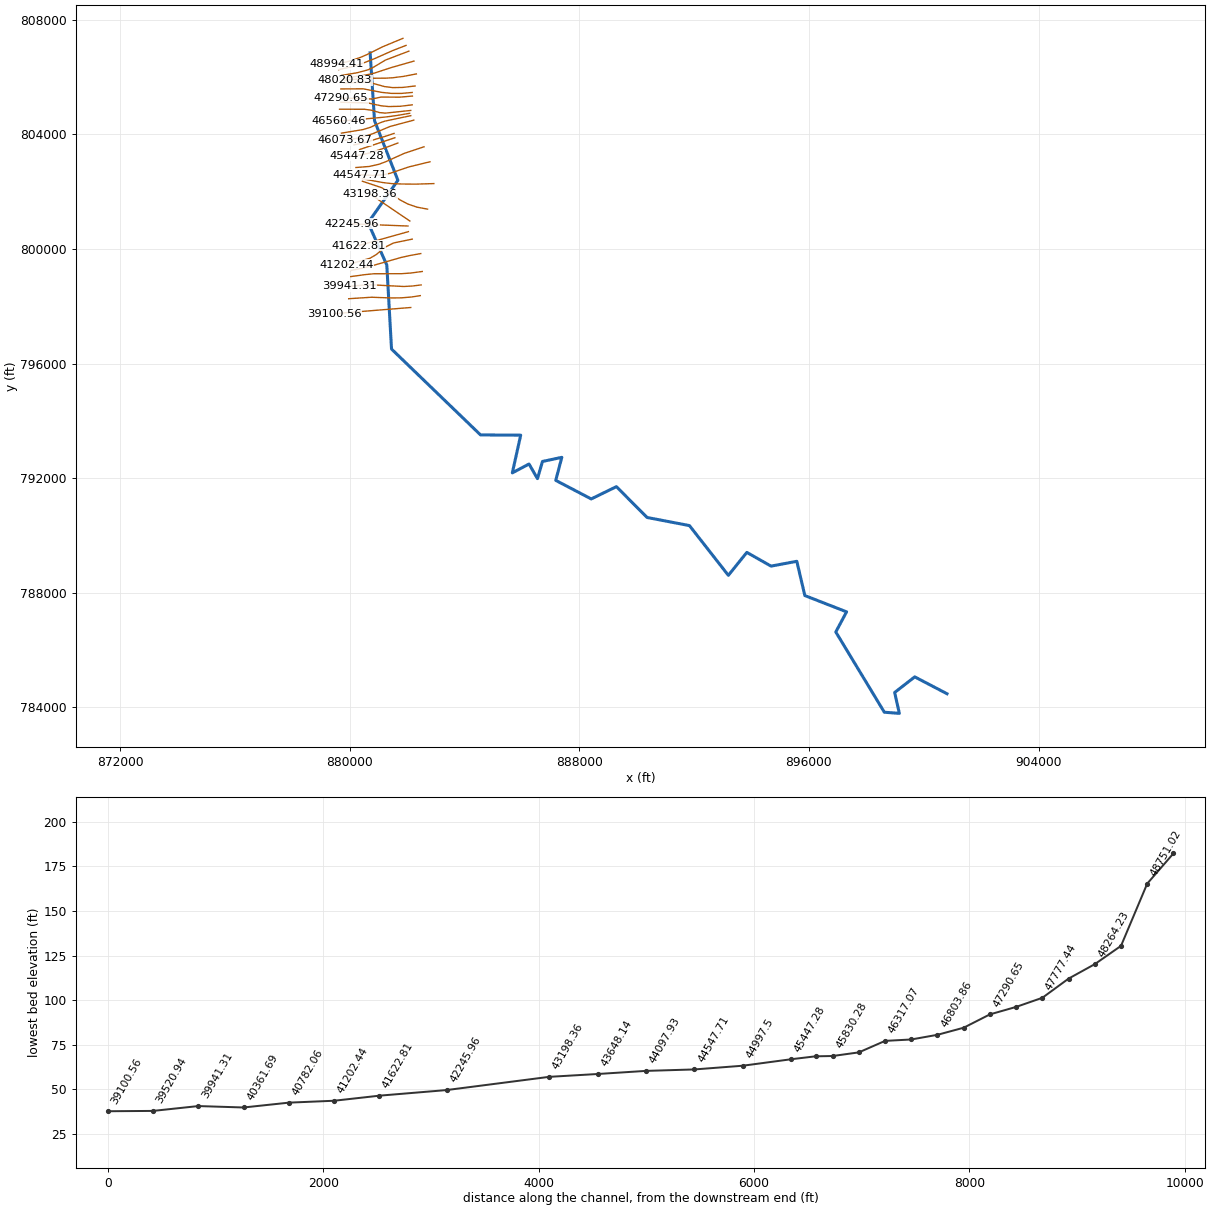
--- 11785_ras.prj (project) ---

Proj Title=11785
Current Plan=p01
Default Exp/Contr=0.3,0.1
English Units
Geom File=g01
Flow File=f01
Plan File=p01
Y Axis Title=Elevation
X Axis Title(PF)=Main Channel Distance
X Axis Title(XS)=Station
BEGIN DESCRIPTION:
RFD model 11785 exported to HEC-RAS
END DESCRIPTION:

--- 11785_ras.p01 (plan) ---

Plan Title=Plan 01
Program Version=4.10
Short Identifier=Plan 01
Geom File=g01
Flow File=f01
Subcritical Flow
Calc Critical at every XS
Secant Critical Depth

--- 11785_ras.f01 (steady flow) ---

Flow Title=Flow 01
Program Version=5.01
Number of Profiles= 6
Profile Names=10yr,25yr,50yr,100yr,100plus,500yr
River Rch & RM=11785,52,48994.41
13660.2317535.2220578.5422227.8532452.6623903.06
River Rch & RM=11785,52,48751.02
13662.0217537.7320581.6522231.37 32457.823906.69
River Rch & RM=11785,52,48507.62
13678.7517560.4320609.2422262.0832502.6423937.19
River Rch & RM=11785,52,48264.23
13747.4117652.3520720.1122384.6332681.5724056.87
River Rch & RM=11785,52,48020.83
13764.6817677.8220752.5522422.1632736.3524097.44
River Rch & RM=11785,52,47777.44
13768.0617682.8120758.9122429.52 32747.1 24105.4
River Rch & RM=11785,52,47534.04
13771.9717688.6220766.3622438.1632759.7224114.81
River Rch & RM=11785,52,47290.65
13775.0517693.1720772.1522444.86 32769.524122.05
River Rch & RM=11785,52,47047.25
13882.1517845.1320961.7322660.5333084.3824346.76
River Rch & RM=11785,52,46803.86
16092.4220863.2124646.7926777.4739095.1128410.26
River Rch & RM=11785,52,46560.46
16106.6720885.5324676.1426812.2939145.9528448.94
River Rch & RM=11785,52,46317.07
16128.0820919.5624721.2126866.0739224.47 28509.3
River Rch & RM=11785,52,46073.67
16129.4320921.7724724.1826869.6439229.6728513.36
River Rch & RM=11785,52,45830.28
16461.22 21408.425343.2427585.48 40274.829265.94
River Rch & RM=11785,52,45672.07
16470.7521424.1525364.4927611.1840312.3229295.46
River Rch & RM=11785,52,45447.28
16479.8921439.6725385.6927637.0440350.0929325.63
River Rch & RM=11785,52, 44997.5
16499.7121473.6725432.3227694.1440433.4529392.64
River Rch & RM=11785,52,44547.71
16522.8921513.2725486.5627760.4740530.28 29470.3
River Rch & RM=11785,52,44097.93
16536.14 21535.725517.1627797.7940584.7729513.78
River Rch & RM=11785,52,43648.14
17516.7122928.8327259.4529784.9543486.0331525.45
River Rch & RM=11785,52,43198.36
17520.3622935.8227269.4929797.6543504.5831541.09
River Rch & RM=11785,52,42245.96
17579.8323040.6827415.2529977.9143767.75 31754.5
River Rch & RM=11785,52,41622.81
17593.3823066.1727451.6130023.6743834.5731810.36
River Rch & RM=11785,52,41202.44
17599.59 23078.827470.1230047.4243869.2331840.22
River Rch & RM=11785,52,40782.06
17645.2723170.7627604.6230219.5444120.5432056.08
River Rch & RM=11785,52,40361.69
17649.2923179.3827617.4830236.2244144.8932077.44
River Rch & RM=11785,52,39941.31
17651.6123184.4727625.1630246.2444159.5132090.38
River Rch & RM=11785,52,39520.94
17655.2623192.58 27637.430262.2344182.8632111.08
River Rch & RM=11785,52,39100.56
17657.0923196.6427643.5330270.2344194.5432121.44
River Rch & RM=11785,52,38711.37
17658.76 23200.427649.23 30277.744205.4432131.14
River Rch & RM=11785,52,38278.26
17660.8823205.1627656.4530287.1544219.2532143.43
River Rch & RM=11785,52,37810.74
21307.64 28819.6 35009.839005.7956948.4541503.98
River Rch & RM=11785,52,37343.22
21312.8828830.2935025.6539026.3656978.4941529.71
River Rch & RM=11785,52, 36875.7
   2131928842.7235044.0639050.2457013.3641559.53
River Rch & RM=11785,52,36729.89
21319.7228844.1935046.2339053.0557017.4641563.04
River Rch & RM=11785,52,36179.42
21325.1528855.19 35062.539074.1457048.2541589.34
River Rch & RM=11785,52,   35402
21337.13 28879.4 35098.339120.5457115.9841647.19
River Rch & RM=11785,52,34739.73
21341.2128887.6935110.5739136.44 57139.241667.04
River Rch & RM=11785,52,34331.57
21530.5329260.0635655.9139838.8658164.7442533.69
River Rch & RM=11785,52,33949.43
21532.4129263.89 35661.639846.2658175.5442542.96
River Rch & RM=11785,52,31855.59
22034.0830215.4537038.28 41606.860745.9444683.79
River Rch & RM=11785,52,28680.56
22054.4930256.3937098.8941685.5760860.9344782.05
River Rch & RM=11785,52,26006.99
22236.2530609.5137615.4842351.8661833.7145602.27
River Rch & RM=11785,52,23204.01
22303.5230741.6637809.7542603.36 62200.945913.57
River Rch & RM=11785,52,20239.01
22369.2230874.9438008.1342862.3662579.0446238.61
River Rch & RM=11785,52,19668.14
22375.3930887.8638027.5842887.9462616.3946271.13
River Rch & RM=11785,52,17114.89
22403.2530946.3838115.8243004.1462786.0446418.99
River Rch & RM=11785,52,12458.81
24514.5334439.18 42891.548880.96 71366.252989.68
River Rch & RM=11785,52,10150.48
24538.9634489.2842966.7948980.1671511.04 53114.5
River Rch & RM=11785,52,6516.288
25129.7235650.3244685.3551223.6674786.5555887.92
River Rch & RM=11785,52,       0
25441.5536268.6445605.5352430.5976548.6657388.16
Boundary for River Rch & Prof#=11785,52,1
Up Type= 0
Dn Type= 2
Boundary for River Rch & Prof#=11785,52,2
Up Type= 0
Dn Type= 2
Boundary for River Rch & Prof#=11785,52,2
Up Type= 0
Dn Type= 2
Boundary for River Rch & Prof#=11785,52,2
Up Type= 0
Dn Type= 2
Boundary for River Rch & Prof#=11785,52,2
Up Type= 0
Dn Type= 2
Boundary for River Rch & Prof#=11785,52,2
Up Type= 0
Dn Type= 2

--- 11785_ras.g01 (geometry) ---

Geom Title=11785
Program Version=4.10

River Reach=11785,52
Reach XY= 30
 880715.20369162806847.564255906880868.191596775804480.630333987
881682.238277997802398.463102503880643.238482715800919.088342711
881295.322483041 799440.63186711881460.294944693796507.766166263
884561.210636068793509.934047521885960.516191622793502.121547531
885667.981469401792185.281269745886250.446747178792495.177103079
886543.849524955791983.892380858886719.196747181792583.718769746
887392.807858292792727.815991966887181.002302735791923.996547515
888417.113413843791275.559047503889294.717580512791704.378491953
890361.557858288790628.857658624891838.988413847790345.003491947
893194.023136066788608.892380854 893838.12035829789409.239603067
894681.870358287788930.072936399895579.439802733789098.475714162
 895858.95369162787902.295158614897312.946747175787334.586825269
896937.078691623786631.461825285  898628.9189694783829.378491931
  899152.3564694783789.664950267898987.425913842784518.831616927
899688.380774957785063.536478048900811.986701655784474.869606303

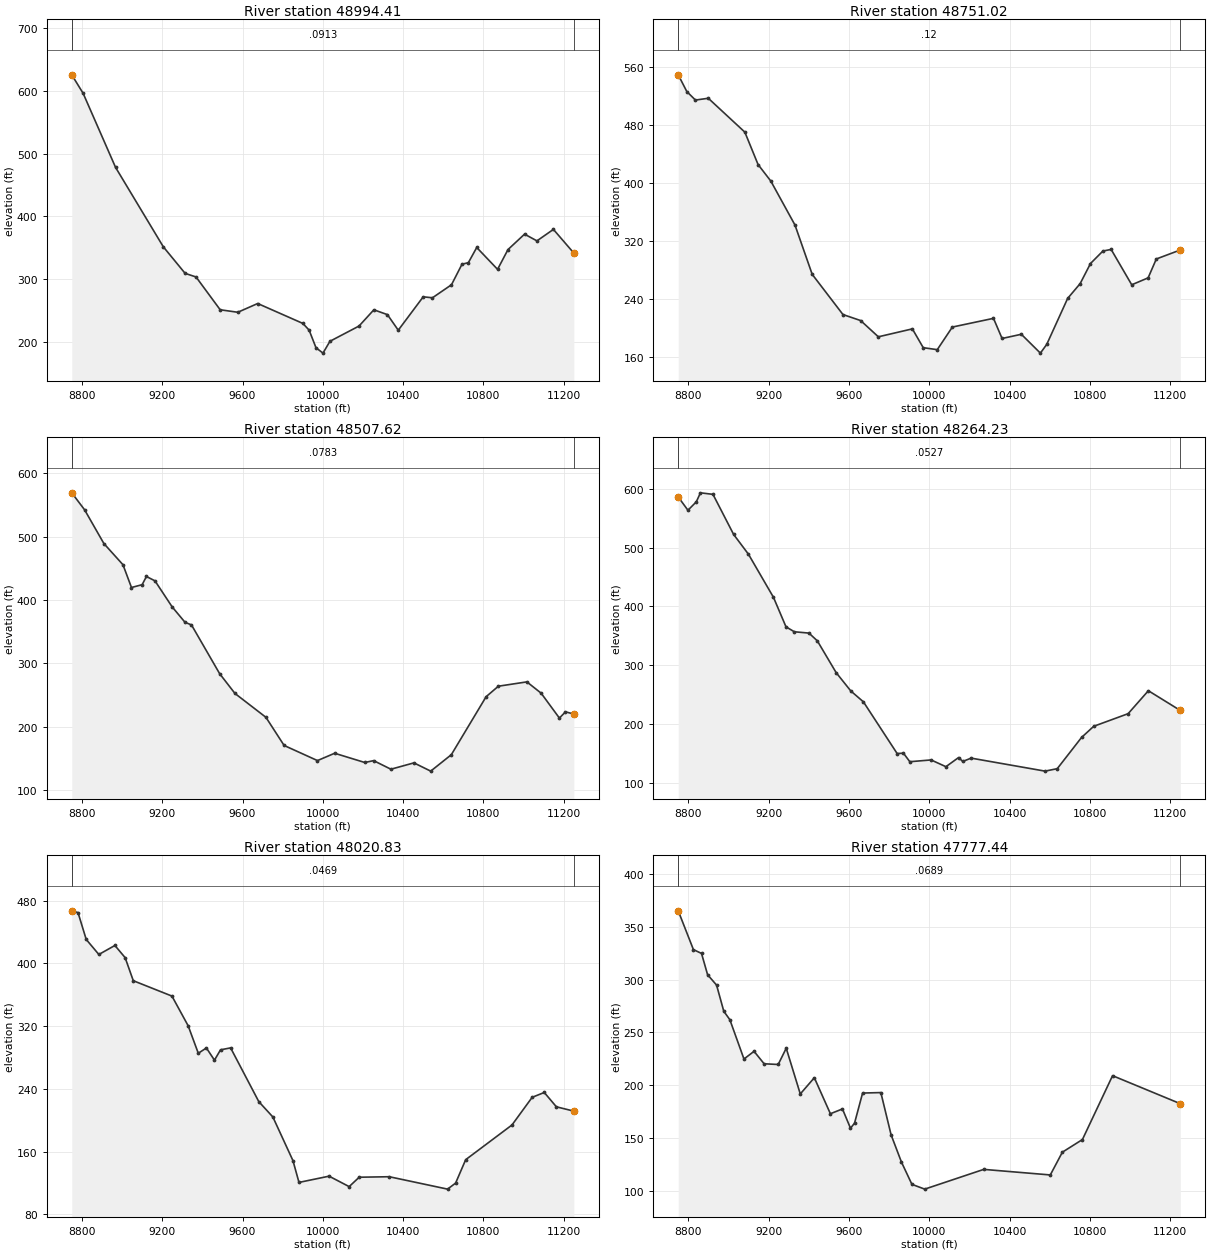
Type RM Length L Ch R = 1 ,48994.41,243.394700,243.394700,243.394700
XS GIS Cut Line= 6
881857.850510952807354.950196907881147.024986115807058.732661484
880613.139463849806791.364863704880386.328855835806693.032947517
879993.739984503806558.985938002879535.727435901806444.835197416
#Sta/Elev= 30
8749.022625.53848805.881595.91928967.259478.10249205.195 351.6039313.896309.2952
9368.268303.55959488.583251.31079576.444247.33349675.504261.27989900.379229.5974
 9931.78 218.9069966.056190.811910000.86 182.24710035.54201.116610180.54225.4195
 10254.4251.248610321.99243.573610375.98 218.76810500.33 271.91910546.52270.4256
10641.27291.157810693.67323.894510725.33326.311410767.03350.509210870.87 315.712
10922.73347.175611005.33371.768811067.04361.045411149.11379.324811250.95 341.585
#Mann= 3 , 0 , 0
8749.022  0.0913       08749.022  0.0913       011250.95  0.0913       0
#XS Ineff= 2 , 0
       0                10189.48       0
Bank Sta=8749.022,11250.95
Exp/Cntr=0.3,0.1

Type RM Length L Ch R = 1 ,48751.02,243.394700,243.394700,243.394700
XS GIS Cut Line= 6
881965.051998033807108.220135858881484.039846164806920.870768394
880893.788621013806656.330250506880402.727448317806462.532334555
880078.832552272806363.569533203879617.768362705806262.391763169
#Sta/Elev= 30
8749.028548.66598791.875 525.5958834.667513.90768898.856516.37669081.044469.6954
 9146.78425.13139210.348402.32899330.835341.73189416.572273.84029569.933218.4404
9658.074210.16269746.216187.79719915.735198.72199969.881 172.81310039.81170.0817
10115.01201.219410320.02213.2217 10362.8185.485710458.77191.277410553.66165.3086
10585.29177.313310689.52240.678310751.76261.013510803.38288.751810865.14305.9163
 10906.3 308.16911008.89259.4533 11090.6268.9901 11131.4294.991711250.97307.4219
#Mann= 3 , 0 , 0
8749.028    0.12       08749.028    0.12       011250.97    0.12       0
#XS Ineff= 2 , 0
       0                10148.65       0
Bank Sta=8749.028,11250.97
Exp/Cntr=0.3,0.1

Type RM Length L Ch R = 1 ,48507.62,243.394700,243.394700,243.394700
XS GIS Cut Line= 6
882065.493184799806908.273614583881247.828654899806596.024032251
880805.758700911806331.288963871880633.015613571806252.709371022
880268.935295409806155.134442687879733.883199063806063.886343166
#Sta/Elev= 30
8749.058 568.8378813.216541.97748908.981488.9652 9004.12 455.5889046.543419.6887
9099.727424.11719121.074437.03959163.769430.14299249.159389.22049313.348364.8737
9345.651360.72939485.919 283.9289562.261252.77089716.581215.1783 9807.23170.8574
9973.373147.022810059.04158.570710209.13144.017210253.26146.951410339.32133.4223
10454.02143.4143 10537.7130.416110640.46156.306810813.82247.672510874.85264.1932
 11016.9271.017911087.78253.273311178.91  214.0111209.29223.822811250.92220.3177
#Mann= 3 , 0 , 0
8749.058  0.0783       08749.058  0.0783       011250.92  0.0783       0
#XS Ineff= 2 , 0
       0                 10138.5       0
Bank Sta=8749.058,11250.92
Exp/Cntr=0.3,0.1

Type RM Length L Ch R = 1 ,48264.23,243.394600,243.394600,243.394600
XS GIS Cut Line= 6
882241.463128077 806560.68724511881428.408395799806327.434250611
880909.893569518806156.442290452880756.032215378806112.674238896
880421.334455244806050.331895255879817.128313889805970.119109719
#Sta/Elev= 30
8749.012585.90878797.327563.40898838.921577.61968859.718592.96938922.109590.3862
9025.053522.28449098.884488.68499223.666415.40429286.057365.27989327.651356.9348
9400.441 354.6689442.105341.52539535.894287.53539608.923256.38199671.819237.8662
 9839.76150.09419871.412150.61719903.063136.160610008.96139.1918 10082.9127.7051
10146.02143.247910166.91136.6291 10208.7142.2562 10576.9120.172910637.73124.3441
10758.92177.421210819.51196.343910990.95217.787411091.78256.775611250.96223.2194
#Mann= 3 , 0 , 0
8749.012  0.0527       08749.012  0.0527       011250.96  0.0527       0
#XS Ineff= 2 , 0
       0                   10225       0
Bank Sta=8749.012,11250.96
Exp/Cntr=0.3,0.1

Type RM Length L Ch R = 1 ,48020.83,243.394700,243.394700,243.394700
XS GIS Cut Line= 6
882325.474968844806112.656755393881876.216930997806026.352871865
881493.870765384805978.292352825881234.733659576805964.013859444
880602.435509015805959.374823339879838.353385095805893.633435527
#Sta/Elev= 30
8749.041466.96928780.177464.68828821.044430.4727    8884411.3117 8964.01422.7862
9014.913407.26139055.585 377.854 9248.21358.24069329.032320.35579379.546285.3193
9419.883292.08769460.111276.53039490.282289.69459540.567292.19529681.087223.6258
9751.209204.04999851.286148.39449881.287120.6227 10031.3128.587110131.31115.2739
10181.31127.240610331.33127.874210621.68112.061410661.79119.753510711.95149.5948
10942.86193.906711043.34229.159211103.63235.310711163.92217.038111250.98211.5215
#Mann= 3 , 0 , 0
8749.041  0.0469       08749.041  0.0469       011250.98  0.0469       0
#XS Ineff= 2 , 0
       0                10283.95       0
Bank Sta=8749.041,11250.98
Exp/Cntr=0.3,0.1

Type RM Length L Ch R = 1 ,47777.44,243.394700,243.394700,243.394700
XS GIS Cut Line= 6
882279.790976027805692.211291912881851.340616359805641.029760931
881499.552078953805634.876189889881217.655752161805670.656501152
880657.683931651805825.498332812879808.294641307805801.324613779
#Sta/Elev= 30
8749.066365.33918824.668328.56188865.101324.91948895.426304.67618940.089 294.897
8976.073270.04879006.291262.03769076.599224.74559126.808232.06029177.016220.2359
9247.155219.56379287.185 234.9869357.221191.60959427.233206.99799507.257172.8469
9567.339177.38289607.423159.11919627.514163.85639667.728192.46639758.691192.9166
9809.739152.83029861.313127.00449913.516105.85169977.356101.319310271.38120.0472
10603.11 114.77410663.11136.350210763.13148.354710913.34208.953311250.92182.3747
#Mann= 3 , 0 , 0
8749.066  0.0689       08749.066  0.0689       011250.92  0.0689       0
#XS Ineff= 2 , 0
       0                10297.55       0
Bank Sta=8749.066,11250.92
Exp/Cntr=0.3,0.1

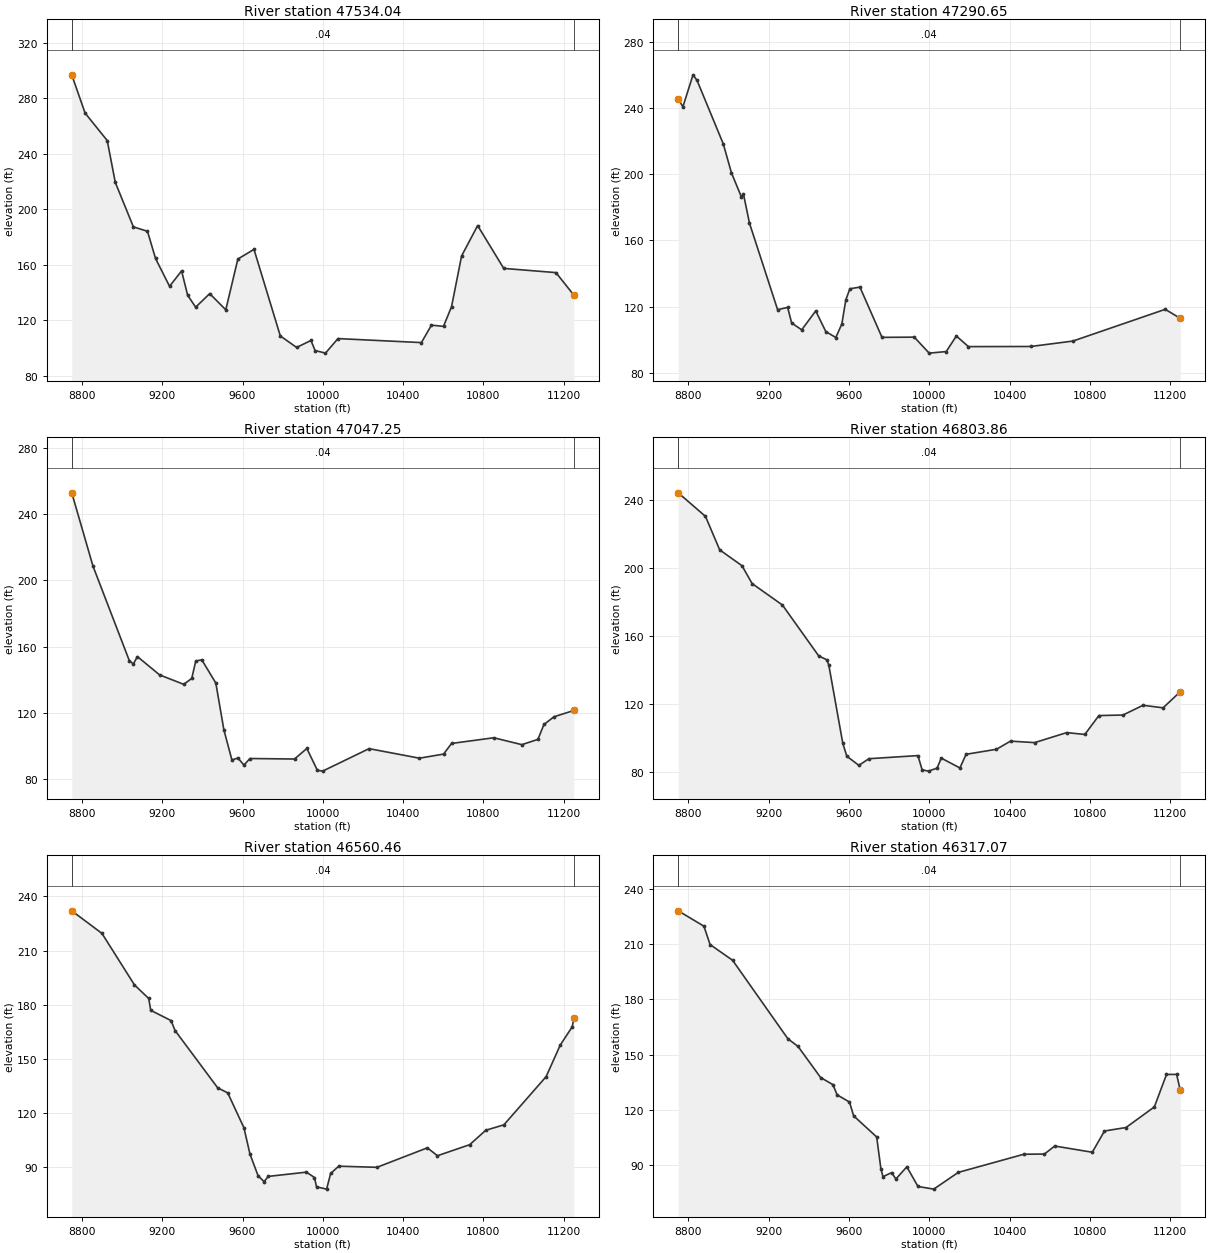
Type RM Length L Ch R = 1 ,47534.04,243.394700,243.394700,243.394700
XS GIS Cut Line= 6
882180.631855138805465.869808357 881805.82028436805432.032547861
881455.240794993805433.092286247881119.176559664805468.370275727
 880471.45340435805592.512999117 879695.95017468805588.790030582
#Sta/Elev= 30
8749.071297.02958815.171269.49488925.803249.59838965.974 219.3969056.172187.2967
9126.325184.12669166.351164.53249236.373144.41729296.375155.54819326.378138.0143
9366.397129.35559436.432139.15049516.539127.4521 9576.71164.11129657.052171.0731
9788.165108.6228 9869.44100.30899940.849105.3136 9961.5698.0890810013.38 96.1982
10075.61106.6904 10491.3103.806510541.38116.381310601.48115.523510641.54129.7513
10691.55166.318710771.56188.254210901.58157.337911161.78154.303211250.93138.0495
#Mann= 3 , 0 , 0
8749.071    0.04       08749.071    0.04       011250.93    0.04       0
#XS Ineff= 2 , 0
       0 9664.71        10295.89       0
Bank Sta=8749.071,11250.93
Exp/Cntr=0.3,0.1

Type RM Length L Ch R = 1 ,47290.65,243.394700,243.394700,243.394700
XS GIS Cut Line= 6
882188.174604746805340.498673787881737.051761116805300.386533609
881099.067630749805305.875954483880779.822943632805236.719391277
880129.478566547805264.609647052 879699.87641301805262.463722877
#Sta/Elev= 30
8749.114 245.3328772.474240.70988822.874259.96768843.034256.55188973.753  218.23
9013.896200.96239064.037186.19329074.052188.05319104.097170.44299244.262118.2374
9294.272119.60159314.272 110.2099364.272106.07489434.293117.50269484.316105.0308
9534.339101.44379564.353109.62679584.362124.23059604.371130.85299654.394131.8576
9764.428101.53349925.294101.66169999.39192.0168810084.5392.9591810134.94102.3637
10194.9995.9498910505.3796.0189310715.6299.2926211175.72 118.45211250.86112.9895
#Mann= 3 , 0 , 0
8749.114    0.04       08749.114    0.04       011250.86    0.04       0
#XS Ineff= 2 , 0
       09778.684        10157.65       0
Bank Sta=8749.114,11250.86
Exp/Cntr=0.3,0.1

Type RM Length L Ch R = 1 ,47047.25,243.394700,243.394700,243.394700
XS GIS Cut Line= 6
882179.454723929805033.078763195881765.824748786804983.333132902
881361.102699778804972.960591648 881100.81424283804999.485507255
880647.320328458805098.187221634879695.994163299805124.989866966
#Sta/Elev= 30
8749.056253.07368854.599208.74129035.965151.4086 9056.06149.44949076.155 153.907
9186.631142.82469306.836137.10539346.878140.68439366.898151.22099396.905151.9494
9466.909137.87669506.917109.61079546.92891.290219576.94492.500149606.99188.18953
9637.03992.183329858.96991.876219920.46498.269589972.68985.08922    9999 84.5435
10230.5298.1541510481.4992.3780110601.6894.8719310641.73101.308310851.85104.7432
10991.87100.576811071.87103.770211101.88 112.78511151.88 117.462 11250.9121.2661
#Mann= 3 , 0 , 0
8749.056    0.04       08749.056    0.04       0 11250.9    0.04       0
#XS Ineff= 2 , 0
       09919.041        10239.72       0
Bank Sta=8749.056,11250.9
Exp/Cntr=0.3,0.1

Type RM Length L Ch R = 1 ,46803.86,243.394600,243.394600,243.394600
XS GIS Cut Line= 6
882128.957089612804837.988551588881247.901595905804744.576828329
881040.006925025804763.394338596880770.126186125804843.720348169
880521.224210497804878.676861717879649.305487571804880.468702992
#Sta/Elev= 30
8749.073244.50958884.761230.64478955.665210.90869066.735201.58319117.155191.0641
9268.274178.42139448.939148.46589489.002146.1801 9499.01143.28059569.05696.97588
9589.05789.368589649.06583.971849699.09587.887719943.32789.724749964.50981.32243
9996.28280.5699910038.76  82.34110059.8688.2422710152.6782.4287810183.27 90.4836
10334.62 93.436310404.8498.2366410525.0397.3686110685.09 103.26510775.09 102.169
 10845.1113.298610965.11113.617511065.15119.3598 11165.2 117.86911250.93127.3805
#Mann= 3 , 0 , 0
8749.073    0.04       08749.073    0.04       011250.93    0.04       0
#XS Ineff= 2 , 0
       09759.001        10261.25       0
Bank Sta=8749.073,11250.93
Exp/Cntr=0.3,0.1

Type RM Length L Ch R = 1 ,46560.46,243.394700,243.394700,243.394700
XS GIS Cut Line= 6
882092.843792981 804738.04686741881671.459454083804665.915271058
881428.689742248 804630.87441062881216.012248801804604.650252987
 880260.83822426 804515.43864397 879607.37862695804463.600342701
#Sta/Elev= 30
8749.016232.01778899.255219.54799061.487190.99769132.422183.49529142.555176.9361
9243.692171.26349263.899165.72169475.926 134.0579526.304131.2104 9606.91111.9337
9637.135 97.30859677.34885.405949707.50782.053969727.61484.988289918.39687.34974
9958.58284.364139968.64279.2296910018.9477.9501510039.0586.6290710079.2690.64032
10270.0390.0324110521.02100.815510571.2296.4354210731.79102.546110812.06110.5295
10902.38113.545211112.99140.245211183.19157.695911243.35 167.88611250.99172.9604
#Mann= 3 , 0 , 0
8749.016    0.04       08749.016    0.04       011250.99    0.04       0
#XS Ineff= 2 , 0
       09602.323                       0
Bank Sta=8749.016,11250.99
Exp/Cntr=0.3,0.1

Type RM Length L Ch R = 1 ,46317.07,243.394700,243.394700,243.394700
XS GIS Cut Line= 6
882130.550445669804655.096456043881230.474131035804465.036244392
881051.319376773804402.208404434880731.084393619804250.730994163
880463.343849964804169.085604648879716.641750728804045.947768947
#Sta/Elev= 30
8749.058228.0177 8877.11219.68828907.707209.73699019.898201.22089295.276158.6821
9346.272154.47639458.658137.64559520.135133.78349540.628128.26489602.466124.3559
9623.133116.87389737.839105.43939758.82288.298539769.314 83.91959812.17986.10009
9833.66382.645949888.15289.251879943.64778.5943410022.3177.1550610144.5886.23045
10471.2296.06257 10573.996.1800210625.14100.5257 10812.397.1447210873.13108.6642
10980.46110.557411121.69121.734611182.11139.315911232.45139.356411250.94130.7109
#Mann= 3 , 0 , 0
8749.058    0.04       08749.058    0.04       011250.94    0.04       0
#XS Ineff= 2 , 0
       0                10348.58       0
Bank Sta=8749.058,11250.94
Exp/Cntr=0.3,0.1

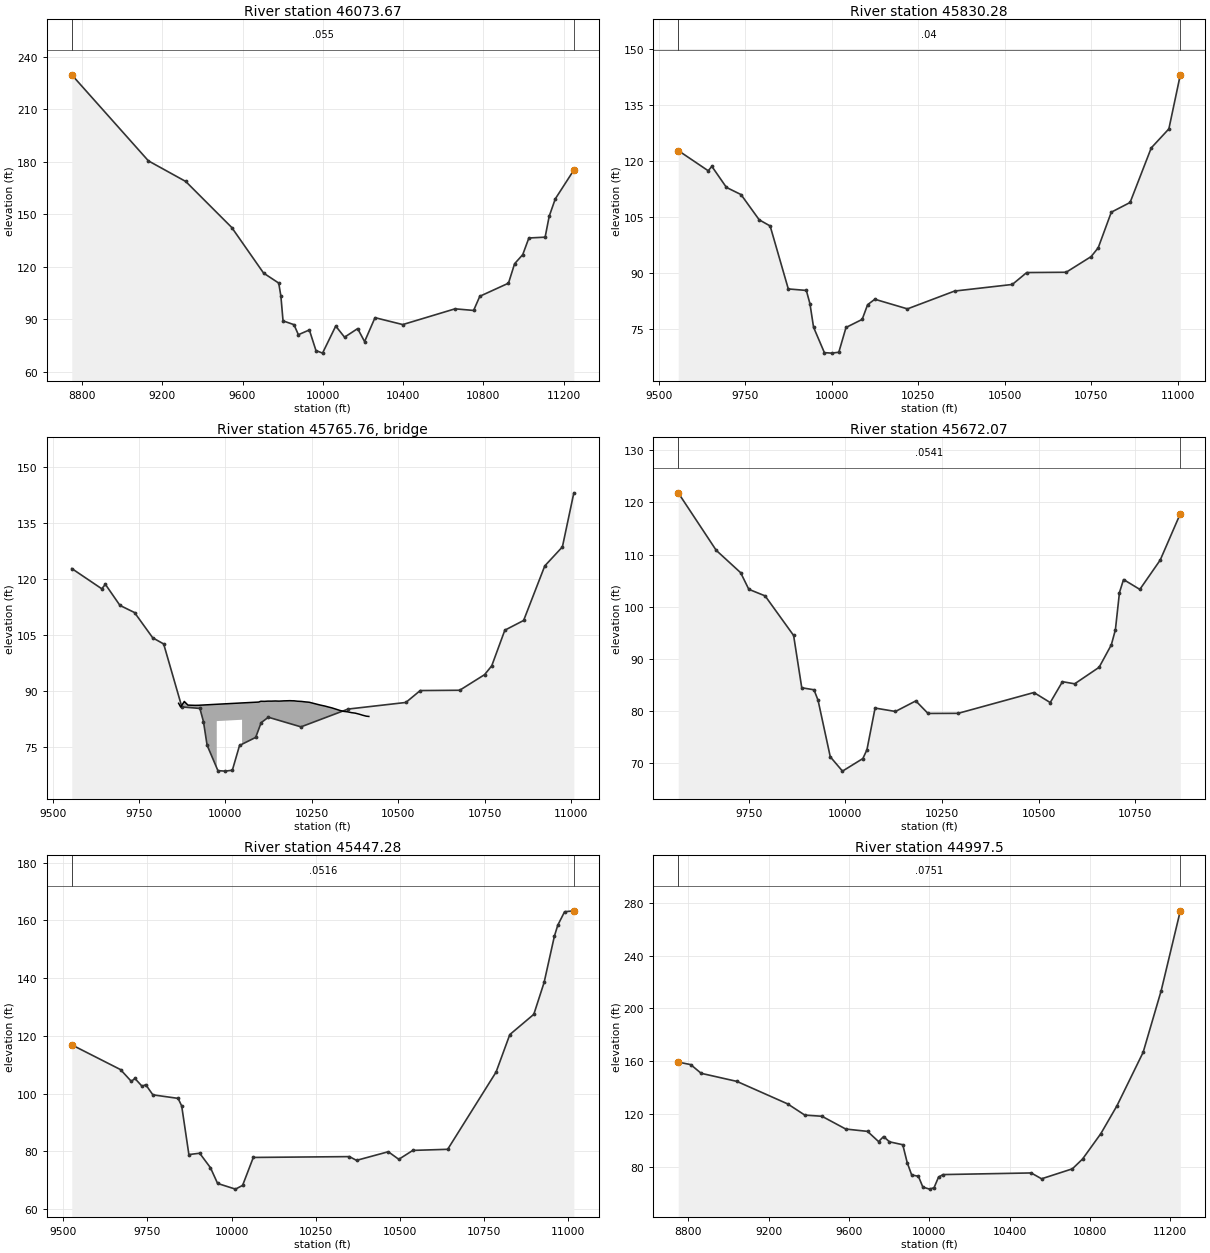
Type RM Length L Ch R = 1 ,46073.67,243.394700,243.394700,243.394700
XS GIS Cut Line= 6
882235.822886307804499.195748693 881413.97613509804280.025793217
880817.148972598804029.985450922880565.847481105803943.682862418
880202.659338801803854.873274379879843.343404859803797.183720237
#Sta/Elev= 30
8749.032229.67639130.955 180.5349316.963168.76689546.313142.46829704.954116.4273
 9780.29110.73549791.052103.32569801.81589.149319856.35186.97181 9878.2481.23935
9932.96183.954579965.794  72.2119998.62870.7177310064.4286.1811510108.2879.82141
10173.6884.7310810208.1877.2925510260.1390.9703110398.4587.0293610658.9796.02097
10751.5295.0982810782.32103.187610925.23110.6672 10955.7121.775210996.34126.9858
11026.81136.483311107.84136.953311128.05148.862311158.35158.803911250.94175.2788
#Mann= 3 , 0 , 0
8749.032   0.055       08749.032   0.055       011250.94   0.055       0
#XS Ineff= 2 , 0
       0                10196.76       0
Bank Sta=8749.032,11250.94
Exp/Cntr=0.3,0.1

Type RM Length L Ch R = 1 ,45830.28,158.210900,158.210900,158.210900
XS GIS Cut Line= 6
881547.277586233804035.629271795  881259.1809122803939.939071512
880705.532084492803770.637348144880515.333439511803716.090226494
880389.092263787 803684.33714958880152.545343721803635.050515624
#Sta/Elev= 30
9555.523122.8631 9642.22117.45179652.757118.63349694.906113.00159737.055111.0913
9789.741104.33159821.352102.69039873.89485.846949926.07285.444079936.50781.88251
9946.94375.600929978.24968.81031 9999.1268.6771810019.9668.9107810040.8175.54187
10087.5277.6958210103.34 81.637710124.1983.0864310218.5180.5121610354.7785.27645
10521.85 87.044210563.4690.2260110677.5390.3046810749.71 94.491510770.31 96.8531
10808.14106.373310862.49108.971110923.67123.564710974.66128.651111007.76143.1128
#Mann= 3 , 0 , 0
9555.523    0.04       09555.523    0.04       011007.76    0.04       0
#XS Ineff= 2 , 0
       09910.734        10118.74       0
Bank Sta=9555.523,11007.76
Exp/Cntr=0.3,0.1

Type RM Length L Ch R = 3 ,45765.76,,,
BEGIN DESCRIPTION:
END DESCRIPTION:
Bridge Culvert--1,0,-1,-1, 0
Deck Dist Width WeirC Skew NumUp NumDn MinLoCord MaxHiCord MaxSubmerge Is_Ogee
69.755450,18.700000,2.6,0, 60, 60, , , 0.95, 0, 0,0,,
 9864.55 9870.43 9880.95 9880.96 9891.49 9902.02 9912.56 9912.83 9923.09 9927.68
 9974.94 9974.9410048.1010048.1010095.9610102.1310104.0910112.6610123.1910133.72
10135.9610144.2510154.7810165.3210167.8410175.8510186.3810193.7910197.0910198.00
10208.2410219.3910220.6310230.5310241.6810243.2710252.8310263.9710265.9110275.12
10286.2710288.5410297.4110308.5610311.1810319.7110330.8510333.8210342.0010353.15
10356.4510364.2910375.4410379.0910386.5910396.4310397.6310406.8310407.8910414.80
   86.82   85.82   87.30   87.31   86.34   86.30   86.27   86.27   86.29   86.32
   86.56   86.56   86.92   86.92   87.15   87.36   87.36   87.34   87.40   87.40
   87.41   87.44   87.40   87.45   87.47   87.49   87.52   87.49   87.49   87.49
   87.38   87.32   87.31   87.20   87.11   87.08   86.85   86.59   86.54   86.33
   86.11   86.06   85.84   85.58   85.50   85.25   84.92   84.85   84.66   84.54
   84.48   84.32   84.19   84.10   83.92   83.64   83.61   83.39   83.37   83.30
 -913.18 -914.18 -912.70 -912.69 -913.66 -913.70 -913.73 -913.73 -913.71 -913.68
 -913.44   82.06   82.42 -913.08 -912.85 -912.64 -912.64 -912.66 -912.60 -912.60
 -912.59 -912.56 -912.60 -912.55 -912.53 -912.51 -912.48 -912.51 -912.51 -912.51
 -912.62 -912.68 -912.69 -912.80 -912.89 -912.92 -913.15 -913.41 -913.46 -913.67
 -913.89 -913.94 -914.16 -914.42 -914.50 -914.75 -915.08 -915.15 -915.34 -915.46
 -915.52 -915.68 -915.81 -915.90 -916.08 -916.36 -916.39 -916.61 -916.63 -916.70
 9864.55 9870.43 9880.95 9880.96 9891.49 9902.02 9912.56 9912.83 9923.09 9927.68
 9971.97 9971.9710045.1310045.1310095.9610102.1310104.0910112.6610123.1910133.72
10135.9610144.2510154.7810165.3210167.8410175.8510186.3810193.7910197.0910198.00
10208.2410219.3910220.6310230.5310241.6810243.2710252.8310263.9710265.9110275.12
10286.2710288.5410297.4110308.5610311.1810319.7110330.8510333.8210342.0010353.15
10356.4510364.2910375.4410379.0910386.5910396.4310397.6310406.8310407.8910414.80
   86.82   85.82   87.30   87.31   86.34   86.30   86.27   86.27   86.29   86.32
   86.54   86.54   86.90   86.90   87.15   87.36   87.36   87.34   87.40   87.40
   87.41   87.44   87.40   87.45   87.47   87.49   87.52   87.49   87.49   87.49
   87.38   87.32   87.31   87.20   87.11   87.08   86.85   86.59   86.54   86.33
   86.11   86.06   85.84   85.58   85.50   85.25   84.92   84.85   84.66   84.54
   84.48   84.32   84.19   84.10   83.92   83.64   83.61   83.39   83.37   83.30
 -913.18 -914.18 -912.70 -912.69 -913.66 -913.70 -913.73 -913.73 -913.71 -913.68
 -913.46   82.04   82.40 -913.10 -912.85 -912.64 -912.64 -912.66 -912.60 -912.60
 -912.59 -912.56 -912.60 -912.55 -912.53 -912.51 -912.48 -912.51 -912.51 -912.51
 -912.62 -912.68 -912.69 -912.80 -912.89 -912.92 -913.15 -913.41 -913.46 -913.67
 -913.89 -913.94 -914.16 -914.42 -914.50 -914.75 -915.08 -915.15 -915.34 -915.46
 -915.52 -915.68 -915.81 -915.90 -916.08 -916.36 -916.39 -916.61 -916.63 -916.70
BR Coef=-1 , 0 , 0 ,, 0 ,,,0.8,0,1,0,
WSPro=,,,, 1 ,,,, 0 ,,,, 0 ,,,,-1 ,-1 ,-1 , 0 , 0 , 0 , 0 , 0
BC Design=,, 0 ,, 0 ,,,,,,

Type RM Length L Ch R = 1 ,45672.07,224.789100,224.789100,224.789100
XS GIS Cut Line= 2
 881578.26234682803884.896081352880345.623457931803472.569692463
#Sta/Elev= 30
9567.223121.85179665.565110.83099728.833106.53879749.922103.36179792.101102.0995
9865.91494.511339887.00384.485979918.63784.099729929.18182.095689960.81571.25776
9992.44968.5090210045.1770.9192910055.72  72.59610076.8180.5965210129.5379.94437
10182.2581.9666110213.89 79.565710291.92 79.587210488.0583.5747210530.2381.65325
10561.8685.6540810593.4985.2446110656.7688.41015 10688.492.7132110698.9495.60251
10709.48102.745610720.03105.232710762.21103.341610814.93108.9593   10867117.8543
#Mann= 3 , 0 , 0
9567.223  0.0541       09567.223  0.0541       0   10867  0.0541       0
#XS Ineff= 2 , 0
       09918.987        10118.78       0
Bank Sta=9567.223,10867
Exp/Cntr=0.3,0.1

Type RM Length L Ch R = 1 ,45447.28,449.783800,449.783800,449.783800
XS GIS Cut Line= 6
881680.522556888803700.219518077881237.055420653803533.783388483
880819.599750676803391.442697385880623.499309398803336.084667961
880492.134689807803304.972491362880257.838506044803261.510487383
#Sta/Elev= 30
9525.322116.8538  9670.2108.28459702.272104.20649712.962105.22559734.343102.4934
9745.033103.06799766.37599.540289841.24698.318499851.93695.696559873.31778.85498
9905.38879.318689937.40274.301699958.66368.8511910011.7666.8845810032.9568.18673
10064.7477.8593810350.3678.1465910371.3876.8455610465.7479.8348410497.0477.21486
10538.7280.2966210642.3180.6793110786.13107.435110826.89120.414310898.23127.4312
 10928.8138.455510959.27 154.452 10969.4158.296410989.66 162.95811017.18163.2772
#Mann= 3 , 0 , 0
9525.322  0.0516       09525.322  0.0516       011017.18  0.0516       0
#XS Ineff= 2 , 0
       0                10268.44       0
Bank Sta=9525.322,11017.18
Exp/Cntr=0.3,0.1

Type RM Length L Ch R = 1 , 44997.5,449.783700,449.783700,449.783700
XS GIS Cut Line= 6
882594.419264019803569.090283157881900.323911431803337.818909029
881257.002540981803046.745906406 881020.13595235802958.541077065
 880690.20932418802882.934108636880219.896596537802845.445126043
#Sta/Elev= 30
8749.026159.38958811.129157.47548863.388150.8857 9041.27144.77679294.552127.7288
9379.785 119.2639465.185118.38759583.704 108.7229692.192106.95819747.411 99.2174
9772.339103.04089801.66499.049729867.92196.845169890.00783.30987 9912.2873.95172
9945.749 72.98859968.06164.7824410001.54 63.247210023.8264.3369310046.1172.32203
10068.3974.2591910507.8675.4946810559.6471.0705510713.1478.6204410763.8486.03188
10854.78105.208810935.27126.322511065.68166.7692 11155.8213.516211250.96273.8562
#Mann= 3 , 0 , 0
8749.026  0.0751       08749.026  0.0751       011250.96  0.0751       0
#XS Ineff= 2 , 0
       0                10627.94       0
Bank Sta=8749.026,11250.96
Exp/Cntr=0.3,0.1

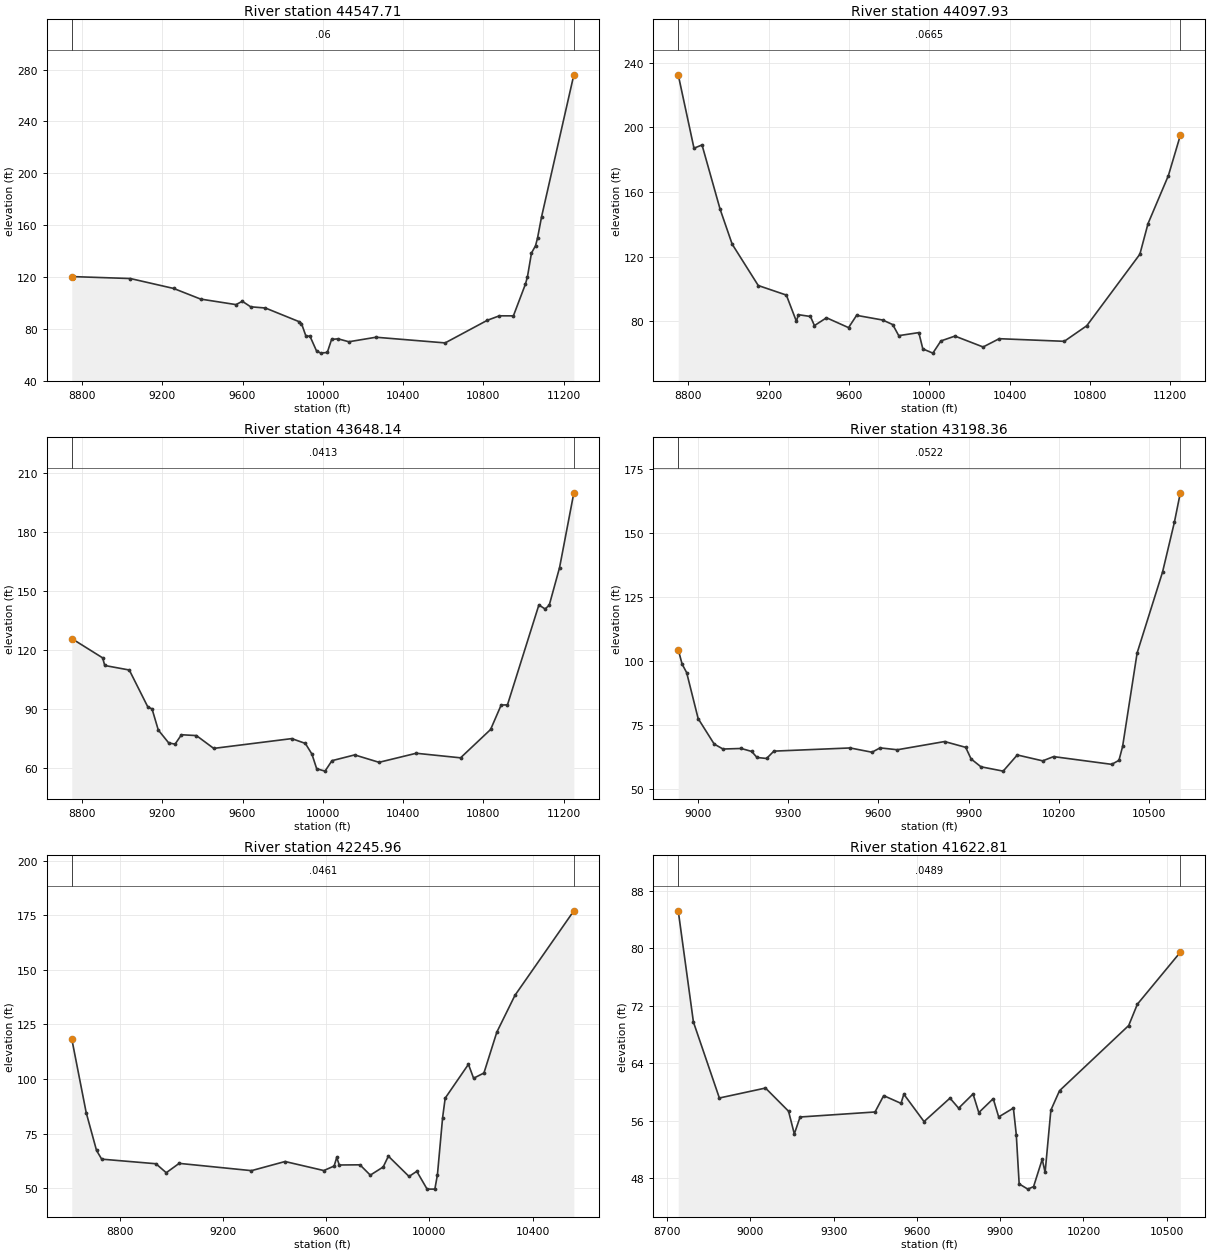
Type RM Length L Ch R = 1 ,44547.71,449.783800,449.783800,449.783800
XS GIS Cut Line= 6
882799.511800583803045.705311294882055.347419903802864.464018723
881435.876405294802651.810120835881212.904586113802596.562772822
880835.813078317802567.711097155880364.466312244802592.774246486
#Sta/Elev= 30
8749.024120.23739040.948118.71849256.869111.05899391.037102.87129567.54398.59651
9598.831101.17599640.54896.908669714.007 95.97619883.16285.350769893.79183.98842
9915.07474.639689936.53374.032819968.72162.84346 9990.1861.1530710022.35 61.6957
10043.7871.7448310075.9472.1919610129.8869.9317610264.8473.4171310609.5369.04067
10819.6586.4931510879.6789.9450910949.7189.91507 11009.8114.458911019.81 120.153
11039.85138.4262 11059.9144.022911069.92149.921611089.98166.295711250.93275.9427
#Mann= 3 , 0 , 0
8749.024    0.06       08749.024    0.06       011250.93    0.06       0
#XS Ineff= 2 , 0
       0                               0
Bank Sta=8749.024,11250.93
Exp/Cntr=0.3,0.1

Type RM Length L Ch R = 1 ,44097.93,449.783700,449.783700,449.783700
XS GIS Cut Line= 6
882933.369135773 802284.41260997882295.674862405802264.843981628
881785.463535943802270.557698884881456.816544173802284.281868659
881153.206612479802321.188362191880446.497154979802451.770651139
#Sta/Elev= 30
8749.011232.49378827.509187.09418867.575189.11458957.689149.35249017.737127.7578
 9147.78102.15659287.79696.251129337.797  80.0349347.79784.124189407.79983.00571
9427.79977.373529487.80182.215419597.80376.111469637.80683.705919767.82180.81726
9817.82778.00084 9847.8371.154319947.85873.036869967.86762.9659710017.8960.34059
10057.9367.8826810128.0170.8807810268.3164.1436710348.6569.2678210672.7467.64881
10784.75 77.274711049.42121.522111090.03 140.44811191.57170.185811250.97 195.019
#Mann= 3 , 0 , 0
8749.011  0.0665       08749.011  0.0665       011250.97  0.0665       0
#XS Ineff= 2 , 0
       09197.777                       0
Bank Sta=8749.011,11250.97
Exp/Cntr=0.3,0.1

Type RM Length L Ch R = 1 ,43648.14,449.783800,449.783800,449.783800
XS GIS Cut Line= 6
882717.414011208801391.943576098882341.869967791801462.492505036
882031.333060008801569.889369212 881758.42531704 801713.90743704
881125.656756077802137.704488699 880445.87249445802365.928993966
#Sta/Elev= 30
8749.039125.90928903.118116.09868913.263 112.2499035.609109.9504 9128.2491.15354
9149.00190.206229180.18879.459119232.38372.891299263.88172.310599295.51977.06871
9370.14776.64779 9456.3870.136059845.14575.108979912.84772.677759945.61167.27458
9969.51359.79623   1001158.5923810045.6763.9061110158.7966.8291110280.1663.06855
10465.4767.6637410686.4265.3488610836.0679.73977 10888.7 92.158910920.1492.24955
11076.69142.996611107.74140.944411128.32142.886111179.78161.977211250.93199.9415
#Mann= 3 , 0 , 0
8749.039  0.0413       08749.039  0.0413       011250.93  0.0413       0
#XS Ineff= 2 , 0
       09865.325                       0
Bank Sta=8749.039,11250.93
Exp/Cntr=0.3,0.1

Type RM Length L Ch R = 1 ,43198.36,952.396600,952.396600,952.396600
XS GIS Cut Line= 2
882098.242131719 800977.77991613880716.124493497801916.046768093
#Sta/Elev= 30
8934.087104.51018946.94298.844898962.17995.482289000.35477.534959053.76767.57391
9083.04465.637069143.47765.855349178.39664.69994  9196.262.325859228.08361.95129
9252.25764.813739506.07566.058539578.59464.390499605.69666.08486  9663.265.35155
9820.32668.562179890.56366.294519908.36761.776219941.19158.6962810015.1956.99833
10062.0663.3148710146.6661.0164110182.9262.6734310376.3159.6487310400.4861.22411
10412.5766.6281510460.91 103.19110545.52134.840410584.93154.303810604.59165.7832
#Mann= 3 , 0 , 0
8934.087  0.0522       08934.087  0.0522       010604.59  0.0522       0
#XS Ineff= 2 , 0
       09809.072                       0
Bank Sta=8934.087,10604.59
Exp/Cntr=0.3,0.1

Type RM Length L Ch R = 1 ,42245.96,623.150600,623.150600,623.150600
XS GIS Cut Line= 2
882030.821759122800803.610620256  880086.8676826800876.649357235
#Sta/Elev= 30
 8614.46118.36178670.32184.616758710.349 67.31098730.36363.311658940.51161.20826
8980.539 57.09559030.575 61.37629310.77258.045399440.86462.22433 9590.9758.09332
9630.99860.159369641.00564.073999651.012 60.63429731.06960.715219771.09755.99066
9821.13259.732249841.14664.682329921.20355.387749951.22457.736029991.25249.58755
10021.2749.5938410031.2856.1949310051.2982.29277 10061.391.2241510151.37106.7209
10171.38100.340510211.41102.737410261.44 121.46310331.49138.263610559.79176.9668
#Mann= 3 , 0 , 0
 8614.46  0.0461       0 8614.46  0.0461       010559.79  0.0461       0
#XS Ineff= 2 , 0
       09393.102                       0
Bank Sta=8614.46,10559.79
Exp/Cntr=0.3,0.1

Type RM Length L Ch R = 1 ,41622.81,420.375200,420.375200,420.375200
XS GIS Cut Line= 2
882047.676852271800606.967866851880305.983893537800118.170165529
#Sta/Elev= 30
8739.84285.250088794.55469.748978888.03159.152899054.21260.540489137.30357.31153
9158.07654.144519178.84856.504699448.89357.205219480.05259.48398 9542.3758.41005
9552.75759.679189625.46155.865439718.93859.136649750.09757.734729802.02959.71778
9822.80257.118269874.73359.063289894.39856.512689947.43857.750899957.82454.04343
9968.21147.17616 9999.3746.4479910020.1446.79895 10051.350.6118110061.6948.78436
10082.4657.4592810113.6260.1698710362.8969.2618110394.0572.2281510548.8279.47491
#Mann= 3 , 0 , 0
8739.842  0.0489       08739.842  0.0489       010548.82  0.0489       0
#XS Ineff= 2 , 0
       09328.475                       0
Bank Sta=8739.842,10548.82
Exp/Cntr=0.3,0.1

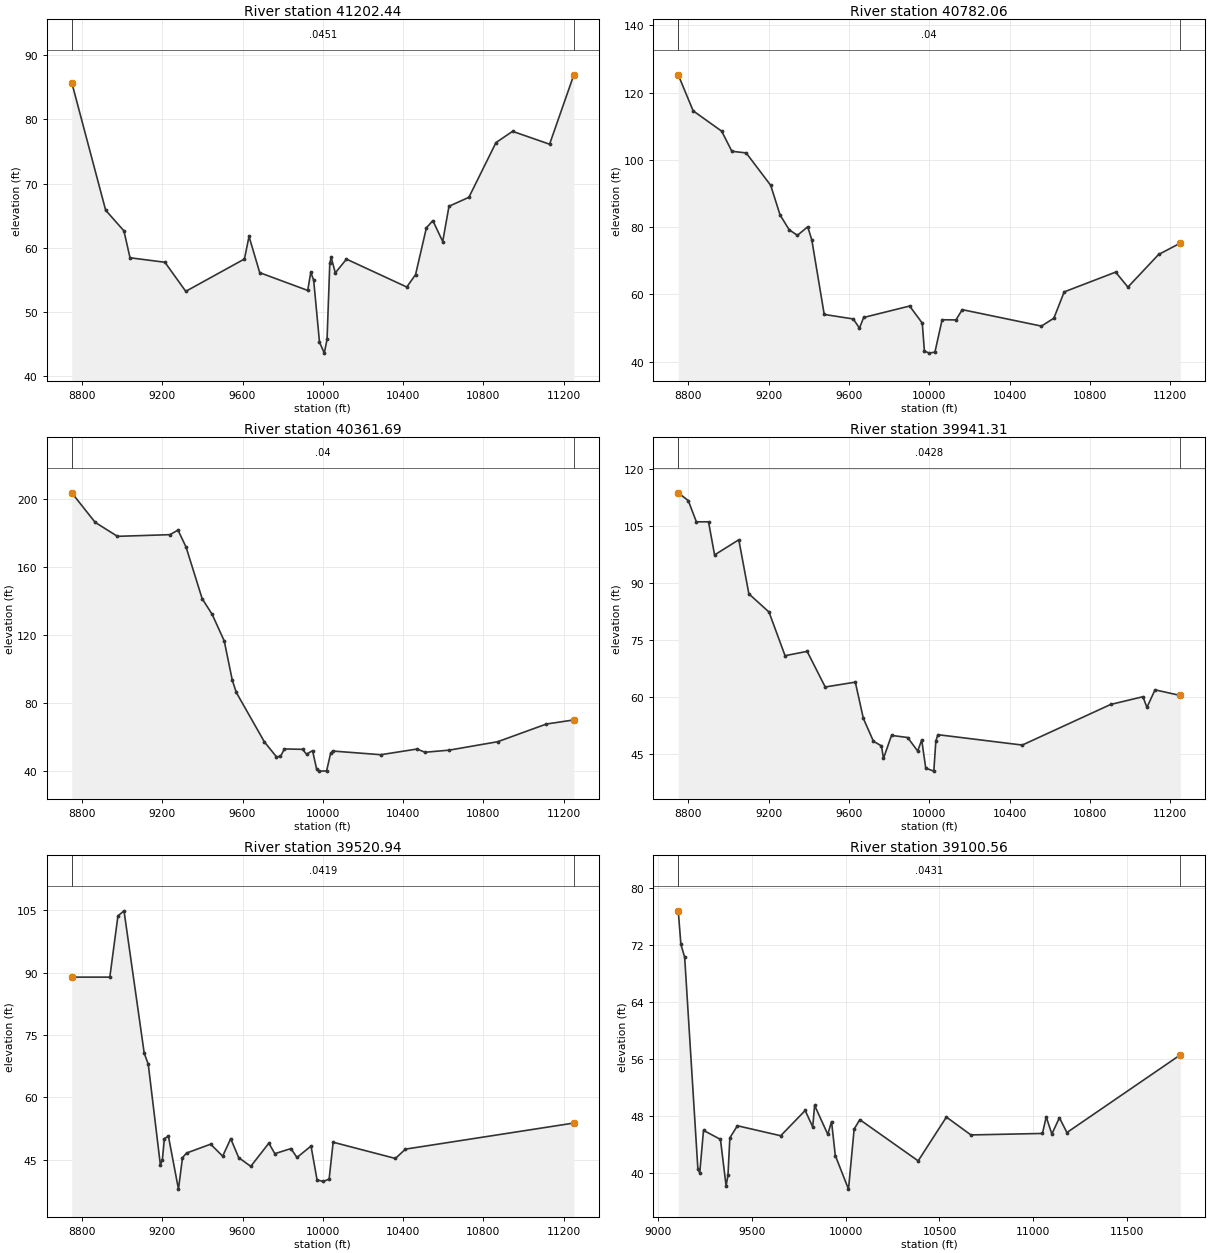
Type RM Length L Ch R = 1 ,41202.44,420.375300,420.375300,420.375300
XS GIS Cut Line= 6
882182.733694828800345.637410815881532.728475699800211.981830929
881232.823641588 800060.67913307880923.327338524799802.374639241
880711.981999081799679.044495503879896.493805048 799443.09479153
#Sta/Elev= 30
8749.05985.746048917.93865.86813 9008.9462.652919039.343 58.45929213.14157.76208
9317.11953.229889609.54558.27035 9632.3361.785969685.66756.13964 9924.8653.37268
9940.02456.200779954.50554.968949983.465 45.312710007.4443.6059410021.1645.76811
10034.8857.6498710041.7258.5128410062.3256.1091810118.0158.2475710418.5153.90192
10462.2255.8408910516.2163.1300510548.3864.2442110597.5360.9881910628.7466.48176
10727.96 67.879810862.9676.4016210945.5778.1565111130.0476.1522511250.9486.95884
#Mann= 3 , 0 , 0
8749.059  0.0451       08749.059  0.0451       011250.94  0.0451       0
#XS Ineff= 2 , 0
       09331.744                       0
Bank Sta=8749.059,11250.94
Exp/Cntr=0.3,0.1

Type RM Length L Ch R = 1 ,40782.06,420.375200,420.375200,420.375200
XS GIS Cut Line= 6
882478.243870336799840.784097421882132.246689297799779.333544965
881799.346472254 799707.30724053880712.121674934799395.501475875
 880421.78866151799327.013708404880048.562437336799253.936141759
#Sta/Elev= 30
8749.018125.26918823.315114.56868965.456108.52059016.295 102.539 9087.47102.0569
9209.87992.409349256.38783.624529301.94679.200299342.96777.559759394.24480.09354
9414.75476.164299476.48554.036119621.09652.701479652.20649.980199672.94653.14095
9902.15756.54121 9965.1451.453189975.63743.197369998.98342.5390610028.1642.85608
10064.0752.4627810132.9652.4092310164.3255.4636410559.0150.5762610620.8552.91641
10672.3360.7431910928.65 66.619910989.9462.1689711142.68 71.858211250.9875.23925
#Mann= 3 , 0 , 0
8749.018    0.04       08749.018    0.04       011250.98    0.04       0
#XS Ineff= 2 , 0
       0  9314.7                       0
Bank Sta=8749.018,11250.98
Exp/Cntr=0.3,0.1

Type RM Length L Ch R = 1 ,40361.69,420.375200,420.375200,420.375200
XS GIS Cut Line= 6
882530.262164119799215.567915899882138.222591763799163.176447616
881815.276671399 799139.00685143880844.162039837799136.826799011
880526.930185033799104.935078368880039.366858647799037.458300563
#Sta/Elev= 30
8749.034203.51778865.539186.1597 8976.68177.92759238.206  178.919278.371181.5919
9318.478171.64689398.629141.31969448.724131.99969508.779116.41089548.79893.38944
9568.80786.125789708.82657.047619768.84148.276489788.84648.472859808.85152.88128
9898.87452.639249918.87949.789999948.88651.872559968.88941.205529978.88939.82707
10018.8939.9276110038.89 50.298210048.8951.6531310288.9249.4817910469.1652.81841
 10509.350.9323510629.8652.1702110871.68 57.130111113.97 67.522511250.9769.95317
#Mann= 3 , 0 , 0
8749.034    0.04       08749.034    0.04       011250.97    0.04       0
#XS Ineff= 2 , 0
       0                               0
Bank Sta=8749.034,11250.97
Exp/Cntr=0.3,0.1

Type RM Length L Ch R = 1 ,39941.31,420.375300,420.375300,420.375300
XS GIS Cut Line= 6
882494.347672111798747.164142712882173.996950763 798707.07612608
881880.587479374 798691.61146674 880792.86489664798748.999147832
880463.667785079798739.825529223879999.574609286798698.530658127
#Sta/Elev= 30
8749.045113.77638798.933111.74258839.371106.16218899.945106.15658930.16397.45249
9050.858 101.4399101.02687.22465 9201.2682.446619281.36170.966469391.40972.10384
9481.40962.740559631.47664.015059671.50154.47978 9721.6148.480219761.70147.25467
9771.72443.955579811.81450.013229892.05549.461339942.263 45.90579962.34748.81326
 9982.4341.4019910022.6240.6219310032.6748.4777510042.73 50.204110463.4847.47216
   1090458.1519811064.5760.1786711084.6757.3792111124.88 61.989911250.9560.51073
#Mann= 3 , 0 , 0
8749.045  0.0428       08749.045  0.0428       011250.95  0.0428       0
#XS Ineff= 2 , 0
       0                               0
Bank Sta=8749.045,11250.95
Exp/Cntr=0.3,0.1

Type RM Length L Ch R = 1 ,39520.94,420.375200,420.375200,420.375200
XS GIS Cut Line= 6
882461.961437586798372.750490365882156.971761332798324.995607805
881801.421527859798296.098525851881464.932128707798291.564429307
880756.337969851798316.552219028879967.741837306798264.635439861
#Sta/Elev= 30
8749.03988.910588938.68788.91058 8979.11103.63989009.366104.86219110.04570.60968
9130.14867.965069190.45843.779929200.509 44.97859210.56150.051329230.63550.65322
9280.73737.904639300.778 45.47769320.81946.582779441.02148.720449501.04445.83318
 9541.0650.039799581.07545.465839641.08343.392129731.08348.95619 9761.0946.43734
9841.14147.660729871.161 45.51869941.28948.263449971.35240.1452210001.4239.75334
10031.4840.3036210051.5349.1901510361.7445.2819410411.7447.5256111250.9753.80566
#Mann= 3 , 0 , 0
8749.039  0.0419       08749.039  0.0419       011250.97  0.0419       0
#XS Ineff= 2 , 0
       0                               0
Bank Sta=8749.039,11250.97
Exp/Cntr=0.3,0.1

Type RM Length L Ch R = 1 ,39100.56,389.195000,389.195000,389.195000
XS GIS Cut Line= 2
882129.164524212797958.579403643879462.873458507797742.709011015
#Sta/Elev= 30
 9108.2376.770479122.441 72.06759142.50670.259769212.73540.611599222.76839.99116
9242.83445.966879333.12844.705349363.22638.165589373.25939.706279383.29244.92594
9423.42346.615679654.17545.213319784.60148.759119824.731 46.45269834.76449.47639
9904.99345.414379925.05947.199199945.12442.4328210015.3537.7232510045.4546.14767
10075.5547.4727210386.5641.6890410537.0547.8347410667.4845.3272911048.7245.53488
11068.7947.8545911098.8945.4545111139.0247.7368811179.15 45.662511783.2556.55958
#Mann= 3 , 0 , 0
 9108.23  0.0431       0 9108.23  0.0431       011783.25  0.0431       0
#XS Ineff= 2 , 0
       0                               0
Bank Sta=9108.23,11783.25
Exp/Cntr=0.3,0.1