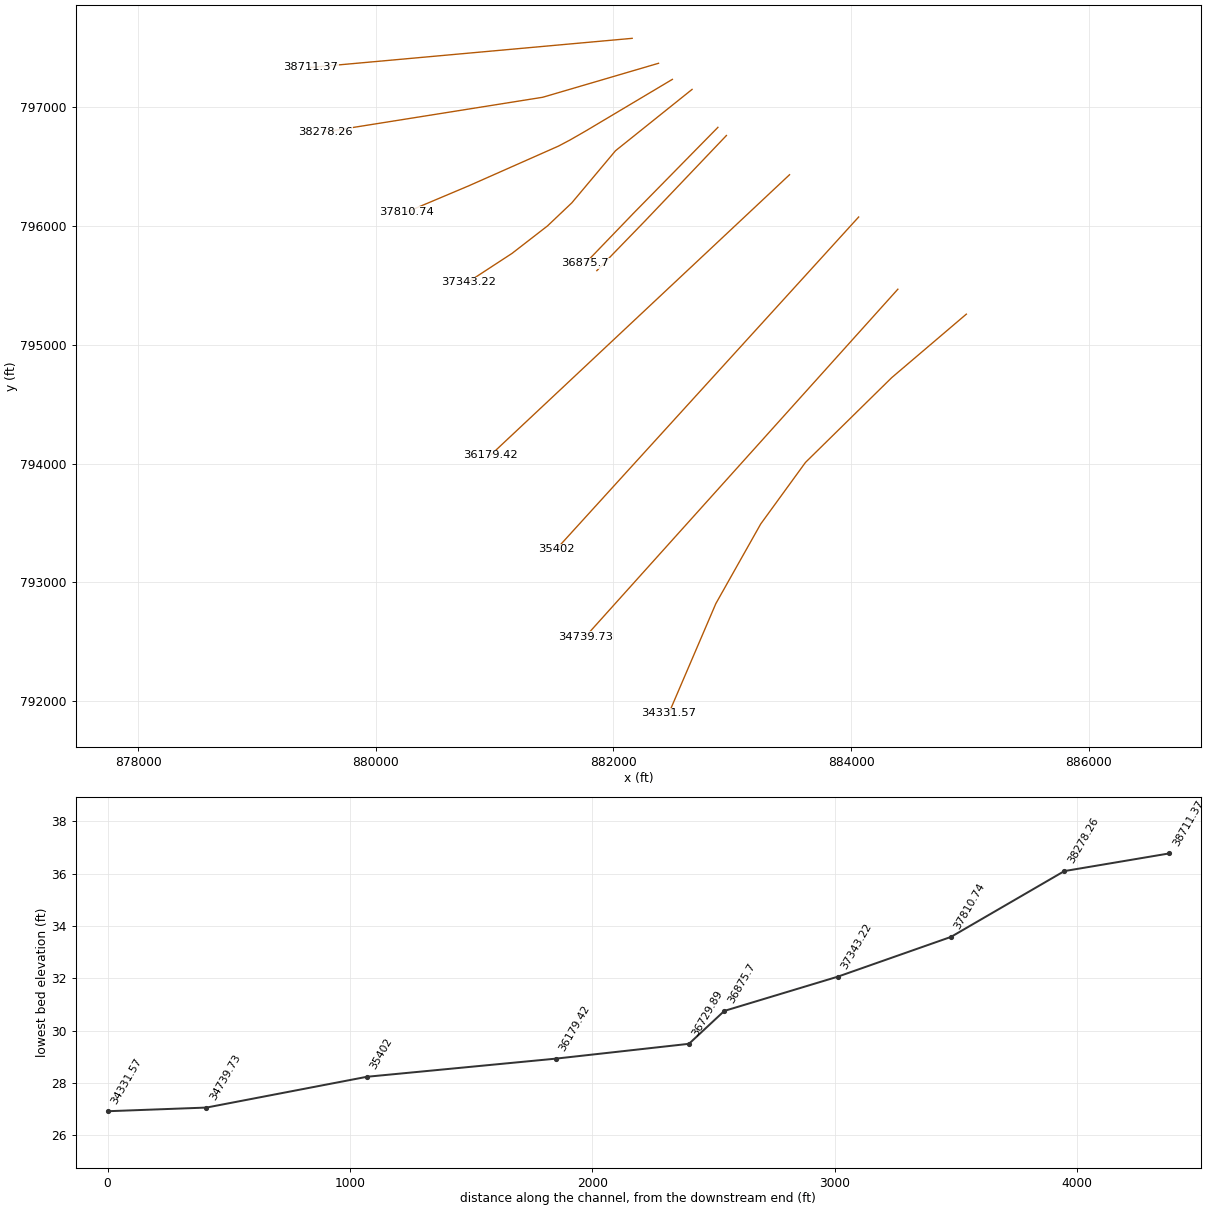
HEC-RAS study 11785_ras.prj: 11785

--- 11785_ras.g01 (geometry) --- (continued)

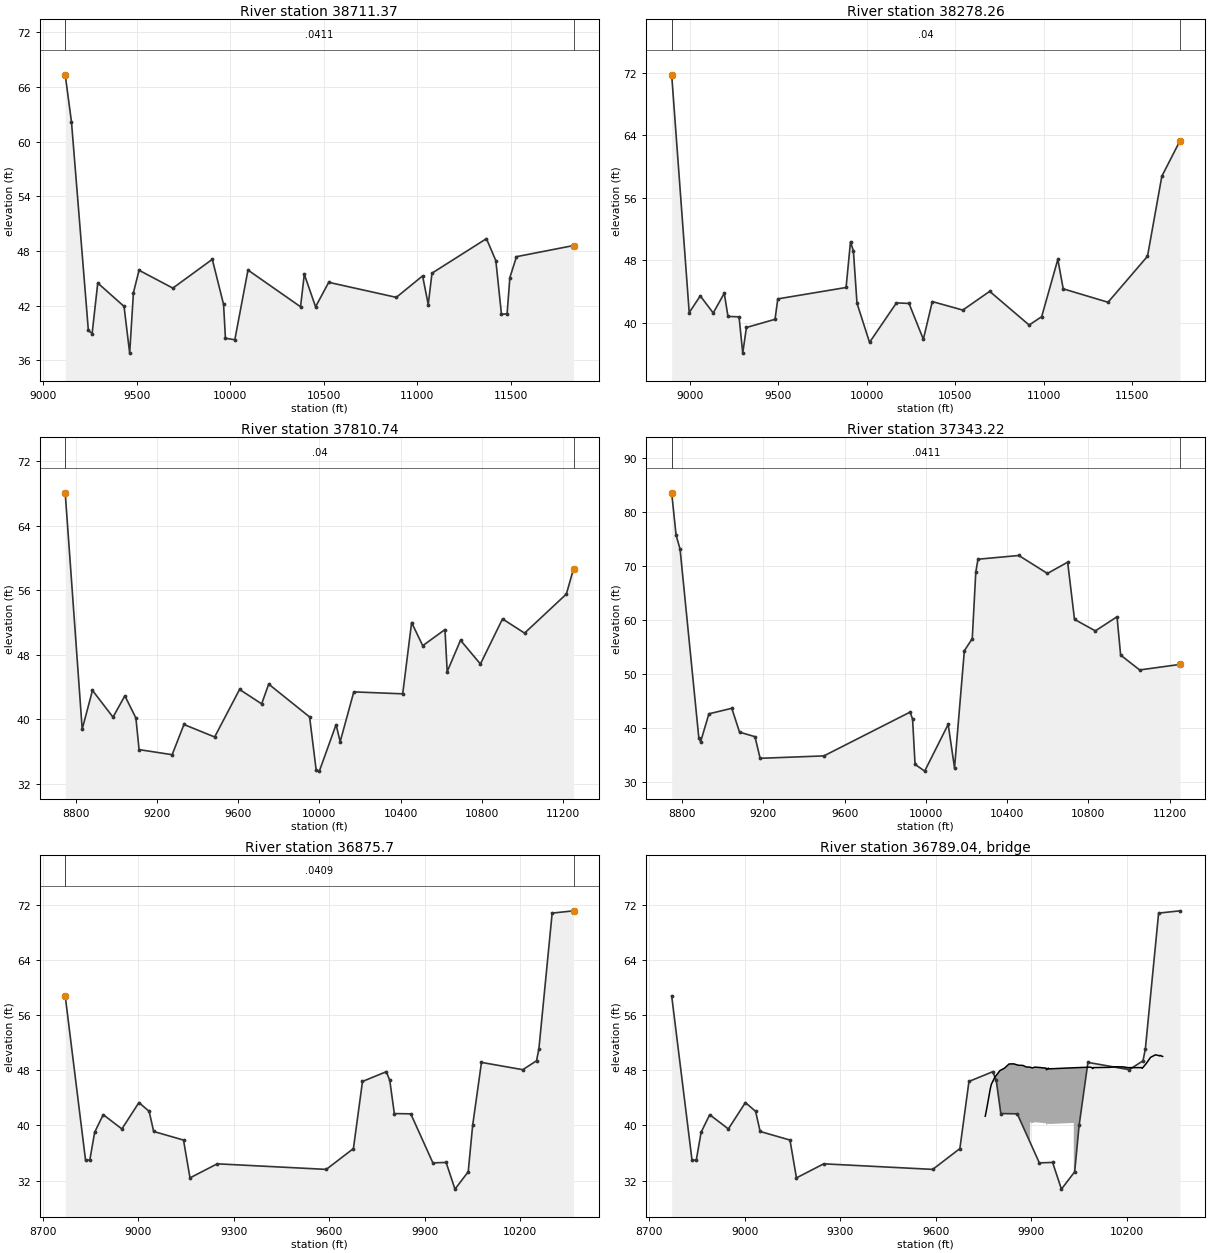
Type RM Length L Ch R = 1 ,38711.37,433.107700,433.107700,433.107700
XS GIS Cut Line= 2
882158.336198892 797579.34763281879451.204788636797334.305565502
#Sta/Elev= 30
9116.84267.327519150.31562.169879240.683 39.26639260.76438.924489290.88744.47137
9431.45941.905449461.58236.773379481.66443.413349511.787 45.86969692.52243.91217
9903.38147.071439963.62642.126019973.66738.4049410023.8738.2438510094.1645.89427
 10375.3 41.862810395.3845.4335510455.63 41.860610525.9244.5475510887.3942.89633
11027.9645.2522711058.0842.1051511078.1645.5516811369.3549.3420411419.5546.92879
11449.68 41.0269 11479.841.0980111494.55 45.0628   1153047.3634311835.0448.58521
#Mann= 3 , 0 , 0
9116.842  0.0411       09116.842  0.0411       011835.04  0.0411       0
#XS Ineff= 2 , 0
       0                               0
Bank Sta=9116.842,11835.04
Exp/Cntr=0.3,0.1

Type RM Length L Ch R = 1 ,38278.26,467.519600,467.519600,467.519600
XS GIS Cut Line= 3
882380.040926456797369.311575118881405.706992161797083.429163259
879573.725822289796791.712416464
#Sta/Elev= 30
8898.23171.729268997.27841.282839059.80843.426469132.75941.239619195.28843.76356
9216.13140.799569278.66140.743739299.504 36.09759320.34739.38002 9481.8440.42839
9497.51443.042249883.11244.501019908.06150.368929924.48249.151269944.73442.48478
10015.6237.4750910167.5142.5298710238.3942.46056 10319.437.8687510370.0342.69772
10542.1741.6084510694.0644.0069410916.83 39.693210987.7140.7700711078.8448.10323
11109.2244.3293711362.3742.6117611585.1448.4986711666.1558.74651 11768.763.28588
#Mann= 3 , 0 , 0
8898.231    0.04       08898.231    0.04       0 11768.7    0.04       0
#XS Ineff= 2 , 0
       0                               0
Bank Sta=8898.231,11768.7
Exp/Cntr=0.3,0.1

Type RM Length L Ch R = 1 ,37810.74,467.519500,467.519500,467.519500
XS GIS Cut Line= 6
882496.698950263797234.079527362881765.747010771796798.646988763
881634.456499745 796723.41917143 881539.09237683796672.854393477
880783.314444071796338.206807623880262.491613154796118.475172927
#Sta/Elev= 30
8749.02268.089248832.65238.786158883.22243.591148984.28440.276119042.60442.92168
9096.91740.174019112.58836.250659275.37535.619189333.47139.364459484.52137.81655
9607.18143.710529715.959 41.92329750.53544.370559951.87440.30079 9984.4433.68394
9999.94633.5827610082.1739.3437310102.4837.2350210169.4443.4090410410.2343.16684
10454.01 52.010110508.7449.1364910618.1951.1361410629.1345.9184910694.7549.81233
10792.6546.8642210901.4352.4566411010.0650.6960911215.7955.5426611250.9958.66124
#Mann= 3 , 0 , 0
8749.022    0.04       08749.022    0.04       011250.99    0.04       0
#XS Ineff= 2 , 0
       0                               0
Bank Sta=8749.022,11250.99
Exp/Cntr=0.3,0.1

Type RM Length L Ch R = 1 ,37343.22,467.519600,467.519600,467.519600
XS GIS Cut Line= 6
882662.398070837797149.511214375882018.152162531796633.444148923
881650.078129289 796194.59140678881445.355193126796000.370014322
881147.067686781795769.318510402880776.816216791795527.636967404
#Sta/Elev= 30
8749.08583.573828770.70975.758968790.35973.158738882.57238.267028891.391 37.4724
8932.28842.666579045.01743.695589083.02739.280039159.04838.435899184.38834.43497
9498.10534.878979922.39842.985939934.68641.710189946.97433.32045 9994.2732.06143
10109.9340.7129710141.2132.6672210189.57 54.351810228.47 56.578410245.8668.88693
10256.5371.2841510457.6971.97599 10598.468.6493510697.9770.7345210731.6960.15408
10834.18 58.021910940.9360.6324310958.7253.5424211052.3850.7906411250.9251.81549
#Mann= 3 , 0 , 0
8749.085  0.0411       08749.085  0.0411       011250.92  0.0411       0
#XS Ineff= 2 , 0
       0                               0
Bank Sta=8749.085,11250.92
Exp/Cntr=0.3,0.1

Type RM Length L Ch R = 1 , 36875.7,145.813400,145.813400,145.813400
XS GIS Cut Line= 3
882879.874724835796830.221197862882172.520736231796110.402821794
881764.312046772795686.613648005
#Sta/Elev= 30
8770.30658.79369 8834.3334.926728847.72834.989948862.86539.009618889.78841.55703
8948.46839.48595 9001.9543.310769034.07242.044549048.339 39.11819142.15237.87169
9162.47832.385329248.08134.42576  9590.833.61718  9676.136.637329704.63446.37542
9779.50847.789849790.34946.535519804.76341.714629856.43341.675239925.856 34.5649
9967.50934.625959995.27930.7542910036.9333.2695910050.8239.9891410078.5949.13903
10208.3748.0811210251.6149.3723110259.0951.1164910300.7470.7974110367.9271.12782
#Mann= 3 , 0 , 0
8770.306  0.0409       08770.306  0.0409       010367.92  0.0409       0
#XS Ineff= 2 , 0
       0                               0
Bank Sta=8770.306,10367.92
Exp/Cntr=0.3,0.1

Type RM Length L Ch R = 3 ,36789.04,,,
BEGIN DESCRIPTION:
END DESCRIPTION:
Bridge Culvert--1,0,-1,-1, 0
Deck Dist Width WeirC Skew NumUp NumDn MinLoCord MaxHiCord MaxSubmerge Is_Ogee
61.586700,22.640000,2.6,0, 38, 38, , , 0.95, 0, 0,0,,
 9755.83 9761.39 9771.60 9774.97 9786.38 9802.14 9815.93 9830.66 9845.18 9859.70
 9874.23 9884.49 9896.92 9896.92 9903.27 9912.07 9946.84 9948.06 9954.20 9954.40
10034.0610034.0610083.9410089.4410094.2210095.6410146.3010165.3810189.3410203.68
10246.7110249.0710261.0610275.4010290.9110304.0910304.8610313.37
   41.33   42.65   45.30   45.96   47.02   47.96   48.29   48.91   48.93   48.73
   48.70   48.48   48.45   48.45   48.33   48.46   48.31   48.07   48.31   48.20
   48.36   48.36   48.45   48.41   48.24   48.38   48.42   48.51   48.49   48.38
   48.38   48.28   48.93   49.87   50.24   50.09   50.16   50.00
 -958.67 -957.35 -954.70 -954.04 -952.98 -952.04 -951.71 -951.09 -951.07 -951.27
 -951.30 -951.52 -951.55   40.45   40.33   40.46   40.31   40.07   40.31   40.20
   40.36 -951.64 -951.55 -951.59 -951.76 -951.62 -951.58 -951.49 -951.51 -951.62
 -951.62 -951.72 -951.07 -950.13 -949.76 -949.91 -949.84 -950.00
 9755.83 9761.39 9771.60 9774.97 9786.38 9802.14 9815.93 9830.66 9843.12 9859.70
 9870.70 9884.49 9898.28 9903.27 9912.07 9946.84 9948.06 9954.20 9954.40 9966.70
 9966.7010083.9410089.4410094.2210095.6410103.8410103.8410165.3810189.3410203.68
10246.7110249.0710261.0610275.4010290.9110304.0910304.8610313.37
   41.33   42.65   45.30   45.96   47.02   47.96   48.29   48.91   48.94   48.73
   48.73   48.48   48.44   48.33   48.46   48.31   48.07   48.31   48.20   48.23
   48.23   48.45   48.41   48.24   48.38   48.35   48.35   48.51   48.49   48.38
   48.38   48.28   48.93   49.87   50.24   50.09   50.16   50.00
 -958.67 -957.35 -954.70 -954.04 -952.98 -952.04 -951.71 -951.09 -951.06 -951.27
 -951.27 -951.52 -951.56 -951.67 -951.54 -951.69 -951.93 -951.69 -951.80 -951.77
   40.23   40.45   40.41   40.24   40.38   40.35 -951.65 -951.49 -951.51 -951.62
 -951.62 -951.72 -951.07 -950.13 -949.76 -949.91 -949.84 -950.00
BR Coef=-1 , 0 , 0 ,, 0 ,,,0.8,0,1,0,
WSPro=,,,, 1 ,,,, 0 ,,,, 0 ,,,,-1 ,-1 ,-1 , 0 , 0 , 0 , 0 , 0
BC Design=,, 0 ,, 0 ,,,,,,

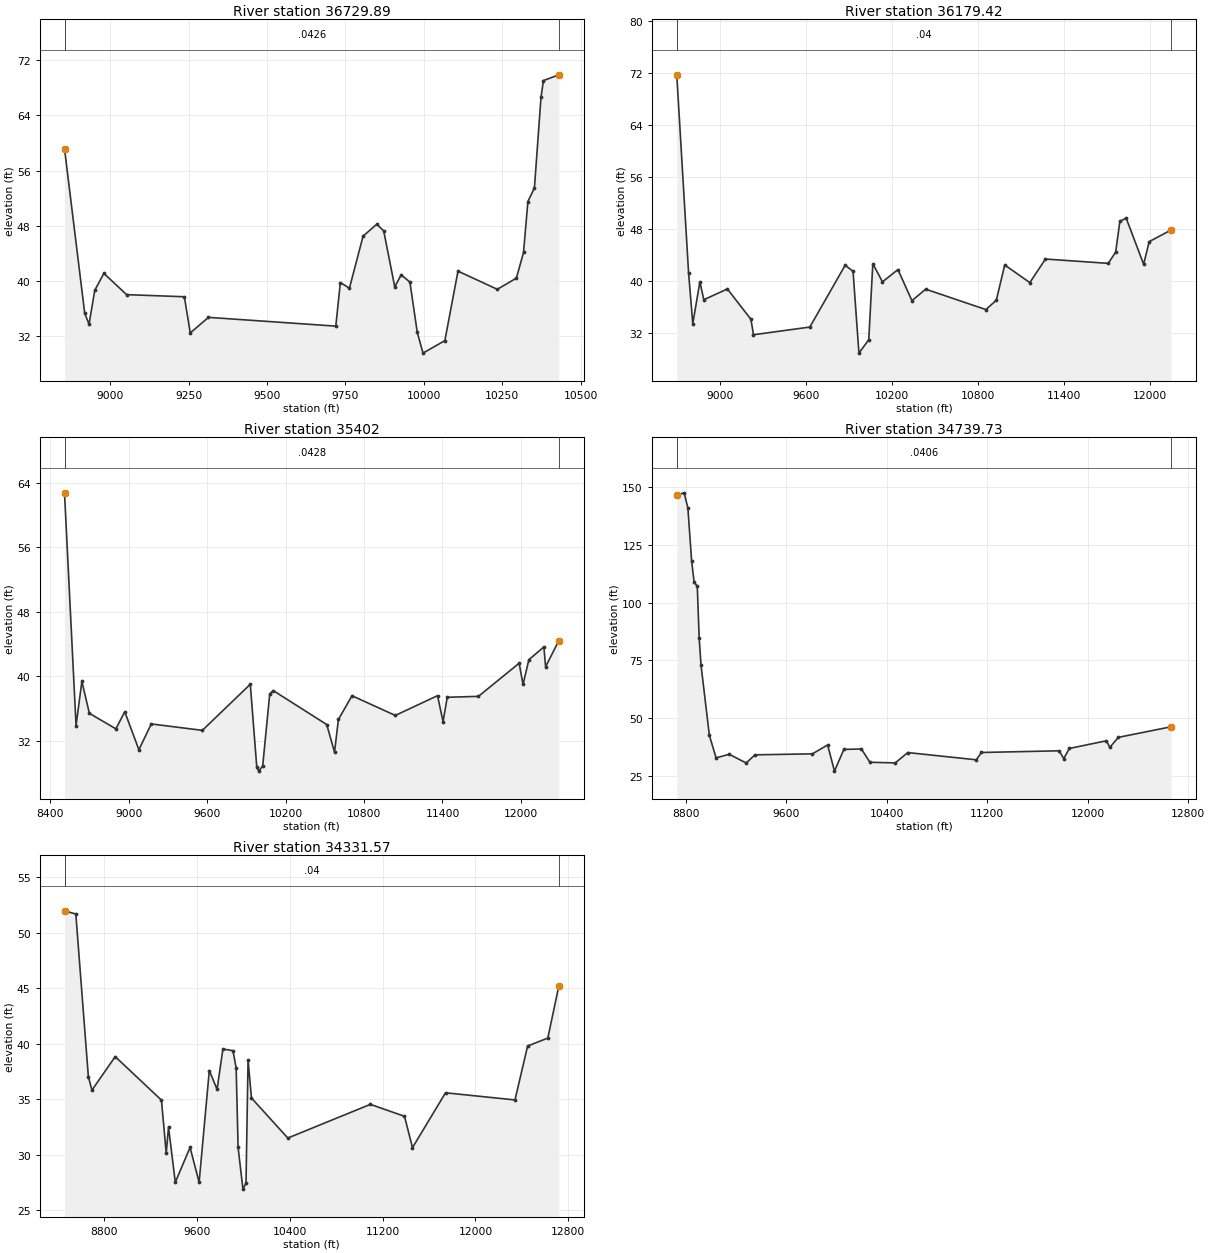
Type RM Length L Ch R = 1 ,36729.89,550.472200,550.472200,550.472200
XS GIS Cut Line= 3
882951.544952755796761.667066808882262.887545347796038.732593874
881860.911049621795624.291710683
#Sta/Elev= 30
8854.46859.18257 8918.9235.270478932.73133.700068950.94838.612698979.944 41.0749
9052.43637.987169236.57137.680299255.41332.429639313.40734.688619719.36133.41745
9733.85939.740289762.85638.931749806.35146.477869849.84648.20418 9872.04 47.2509
9907.32739.108299927.76440.862529955.62639.809189979.14232.49891 9997.4229.49711
10067.0831.3151310108.8741.3991310234.2538.7616610295.1340.3826410317.8344.11412
10331.7751.5073910352.5853.4733610373.56 66.639710381.31 69.061510430.2769.89602
#Mann= 3 , 0 , 0
8854.468  0.0426       08854.468  0.0426       010430.27  0.0426       0
#XS Ineff= 2 , 0
       0                               0
Bank Sta=8854.468,10430.27
Exp/Cntr=0.3,0.1

Type RM Length L Ch R = 1 ,36179.42,777.417400,777.417400,777.417400
XS GIS Cut Line= 2
883482.774004204796431.535370255880965.412893092794070.424259143
#Sta/Elev= 30
8697.78471.658988780.42541.22678 8809.66 33.44138859.25539.887338886.67637.12743
9051.199 38.78299215.72234.121639233.569 31.7505 9627.0332.931849873.81542.42723
9928.65641.491689969.78728.9296310038.3430.9856910066.7742.6467210134.3139.87664
10242.18 41.757810339.9636.9805110435.9438.7512710856.1235.6168510929.2137.05128
10987.6842.4640811163.0939.7568111272.2643.3766211710.99 42.709211762.4144.44802
11791.64 49.1472 11835.549.6684311957.7842.5732211996.2946.0430412149.1547.83488
#Mann= 3 , 0 , 0
8697.784    0.04       08697.784    0.04       012149.15    0.04       0
#XS Ineff= 2 , 0
       0                10223.04       0
Bank Sta=8697.784,12149.15
Exp/Cntr=0.3,0.1

Type RM Length L Ch R = 1 ,   35402,662.268700,662.268700,662.268700
XS GIS Cut Line= 2
884064.371226426796075.632592477881520.968448648793280.493703588
#Sta/Elev= 30
8510.08562.782468598.302 33.89368642.87739.373188700.22435.410188903.029 33.4869
8970.63135.607199078.79330.897369173.43534.095149564.104 33.29969930.57239.02127
9980.141 28.7203    999528.2382710025.2128.87195 10079.337.8408410106.3438.23353
10515.0534.0174110574.4830.58985 10604.234.6558510708.21  37.59511039.2435.15147
11361.9837.6049211404.2934.3833811436.2737.4061311674.6937.5180211986.0441.63089
12015.7638.9911912060.3342.0693412174.9443.6499312188.4641.19468 12289.244.42941
#Mann= 3 , 0 , 0
8510.085  0.0428       08510.085  0.0428       0 12289.2  0.0428       0
#XS Ineff= 2 , 0
       0                10564.57       0
Bank Sta=8510.085,12289.2
Exp/Cntr=0.3,0.1

Type RM Length L Ch R = 1 ,34739.73,408.155400,408.155400,408.155400
XS GIS Cut Line= 2
884394.232337537795467.993703588881764.024004204792542.646481366
#Sta/Elev= 30
    8729146.55388787.678147.49498817.592140.92268847.505117.83358867.502 108.798
8892.375107.08218907.33184.687678922.28872.824368988.53142.531619041.94132.79665
9146.63834.356659281.24830.588519351.61934.109639808.83934.546589929.86838.38584
 9984.2127.0613910058.99 36.471210198.8236.6400710266.0630.9072510467.7830.60703
10567.5235.0920211113.2631.9592711153.61 35.1251 11772.235.8595811808.9232.50345
11853.7936.8687412148.73 40.198312175.6337.3227112242.8741.6717112662.9146.24685
#Mann= 3 , 0 , 0
    8729  0.0406       0    8729  0.0406       012662.91  0.0406       0
#XS Ineff= 2 , 0
       0                11053.42       0
Bank Sta=8729,12662.91
Exp/Cntr=0.3,0.1

Type RM Length L Ch R = 1 ,34331.57,382.145000,382.145000,382.145000
XS GIS Cut Line= 6
884970.624662835795258.170291662884341.880384429794722.989149924
883616.833170256 794010.26832354  883239.6767882793491.678298214
882862.520406144792822.225720064882466.506204986791898.192584028
#Sta/Elev= 30
8460.13251.966598557.59151.680878665.58637.049558696.44235.827058897.006 38.8451
9295.22634.929539336.29730.165439356.071 32.49889414.63827.537549541.65230.67659
9619.62427.527849707.47537.594849774.38935.896399824.60939.529419911.29239.38182
9938.67337.833789955.46230.681729997.15426.9210410023.6927.4667210041.2438.54417
10070.6335.1217910383.78 31.517411094.8334.5496411388.8733.4754811457.5830.65522
11742.3335.5894812340.7134.9476912449.5139.8020312623.5840.5148912718.0345.19825
#Mann= 3 , 0 , 0
8460.132    0.04       08460.132    0.04       012718.03    0.04       0
#XS Ineff= 2 , 0
       09092.046        11167.35       0
Bank Sta=8460.132,12718.03
Exp/Cntr=0.3,0.1