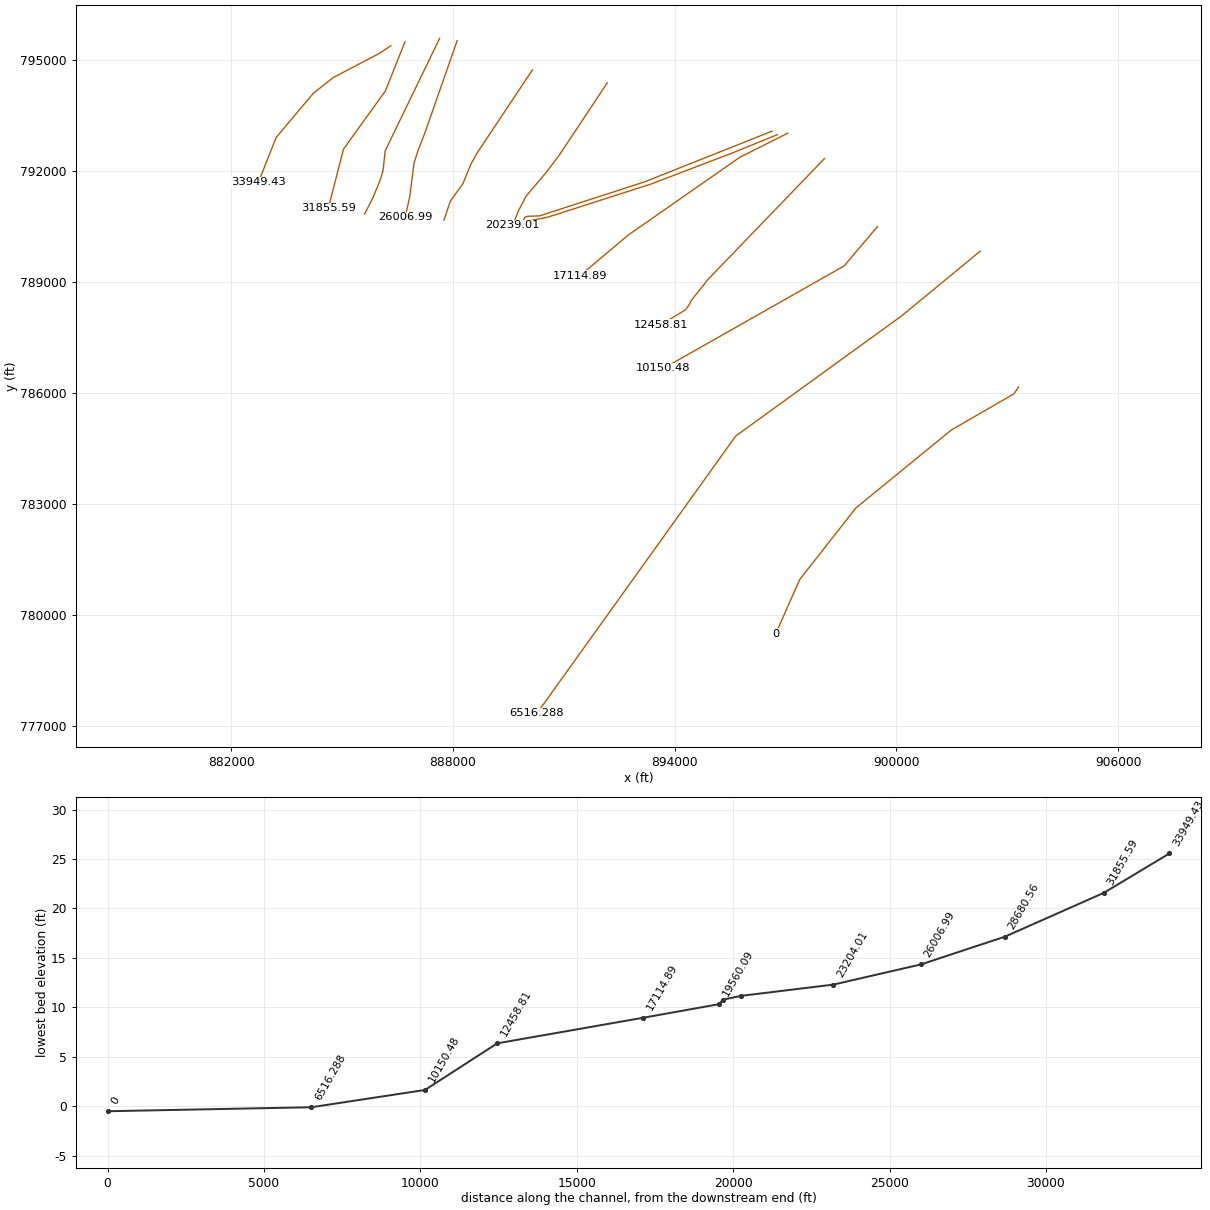
HEC-RAS study 11785_ras.prj: 11785

--- 11785_ras.g01 (geometry) --- (continued)

Type RM Length L Ch R = 3 ,34202.51,,,
BEGIN DESCRIPTION:
END DESCRIPTION:
Bridge Culvert--1,0,-1,-1, 0
Deck Dist Width WeirC Skew NumUp NumDn MinLoCord MaxHiCord MaxSubmerge Is_Ogee
135.572500,111.000000,2.6,0, 60, 60, , , 0.95, 0, 0,0,,
 7997.94 8004.79 8012.66 8028.37 8067.87 8122.68 8189.34 8216.99 8377.46 8445.09
 8478.91 8531.77 8569.08 8637.55 8671.97 8698.36 8752.28 8800.35 8821.12 8832.60
 8841.15 8889.96 8901.94 8913.19 9045.70 9128.73 9128.7311158.7311158.7311238.14
11360.0011382.0611426.1711462.2311514.4011547.4911557.0811690.8611723.9511812.18
11953.7811986.1611996.9612007.7612018.5512029.3512040.1512050.9412061.7412072.54
12076.8612083.3312094.1312103.3912126.5212191.3012363.9312439.4312450.2212648.38
   52.01   51.82   52.00   51.54   52.51   52.48   52.98   52.90   54.51   54.77
   55.27   55.38   55.87   56.10   56.48   56.36   56.80   56.37   56.71   57.30
   57.20   58.17   58.09   58.39   59.35   59.03   59.03   50.97   50.97   50.77
   51.27   51.15   51.66   51.64   52.38   52.48   52.27   53.36   53.41   54.43
   55.39   56.05   53.49   49.89   37.05   34.99   34.19   33.81   35.40   40.41
   45.66   52.39   56.14   56.71   56.30   57.01   57.82   58.46   58.75   59.82
 -947.99 -948.18 -948.00 -948.46 -947.49 -947.52 -947.02 -947.10 -945.49 -945.23
 -944.73 -944.62 -944.13 -943.90 -943.52 -943.64 -943.20 -943.63 -943.29 -942.70
 -942.80 -941.83 -941.91 -941.61 -940.65 -940.97   51.03   42.97 -949.03 -949.23
 -948.73 -948.85 -948.34 -948.36 -947.62 -947.52 -947.73 -946.64 -946.59 -945.57
 -944.61 -943.95 -946.51 -950.11 -962.95 -965.01 -965.81 -966.19 -964.60 -959.59
 -954.34 -947.61 -943.86 -943.29 -943.70 -942.99 -942.18 -941.54 -941.25 -940.18
 7997.94 8004.79 8012.66 8028.37 8067.87 8122.68 8189.34 8216.99 8377.46 8445.09
 8478.91 8531.77 8569.08 8637.55 8671.97 8698.36 8752.28 8763.75 8786.70 8800.35
 8821.12 8832.60 8841.15 8867.02 8980.52 8980.52 9053.4711010.5211010.5211215.82
11360.0011382.0611426.1711462.2311514.4011547.4911557.0811690.8611723.9511812.18
11953.7811986.1611996.9612007.7612018.5512029.3512040.1512050.9412061.7412072.54
12076.8612083.3312094.1312103.3912126.5212191.3012363.9312439.4312450.2212648.38
   52.01   51.82   52.00   51.54   52.51   52.48   52.98   52.90   54.51   54.77
   55.27   55.38   55.87   56.10   56.48   56.36   56.80   56.57   56.66   56.37
   56.71   57.30   57.20   57.86   58.87   58.87   59.39   51.44   51.44   50.78
   51.27   51.15   51.66   51.64   52.38   52.48   52.27   53.36   53.41   54.43
   55.39   56.05   53.49   49.89   37.05   34.99   34.19   33.81   35.40   40.41
   45.66   52.39   56.14   56.71   56.30   57.01   57.82   58.46   58.75   59.82
 -947.99 -948.18 -948.00 -948.46 -947.49 -947.52 -947.02 -947.10 -945.49 -945.23
 -944.73 -944.62 -944.13 -943.90 -943.52 -943.64 -943.20 -943.43 -943.34 -943.63
 -943.29 -942.70 -942.80 -942.14 -941.13   50.87   51.39   43.44 -948.56 -949.22
 -948.73 -948.85 -948.34 -948.36 -947.62 -947.52 -947.73 -946.64 -946.59 -945.57
 -944.61 -943.95 -946.51 -950.11 -962.95 -965.01 -965.81 -966.19 -964.60 -959.59
 -954.34 -947.61 -943.86 -943.29 -943.70 -942.99 -942.18 -941.54 -941.25 -940.18
Pier Skew, UpSta & Num, DnSta & Num=  ,9465.73, 2 ,9317.52, 2 , 0 , 0 , 0 ,,
    4.00    4.00
 -942.33   57.67
    4.00    4.00
 -941.73   58.27
Pier Skew, UpSta & Num, DnSta & Num=  ,9804.73, 2 ,9656.52, 2 , 0 , 0 , 0 ,,
    4.00    4.00
 -943.69   56.31
    4.00    4.00
 -943.10   56.90
Pier Skew, UpSta & Num, DnSta & Num=  ,10143.73, 2 ,9995.52, 2 , 0 , 0 , 0 ,,
    4.00    4.00
 -945.06   54.94
    4.00    4.00
 -944.46   55.54
Pier Skew, UpSta & Num, DnSta & Num=  ,10482.73, 2 ,10334.52, 2 , 0 , 0 , 0 ,,
    4.00    4.00
 -946.43   53.57
    4.00    4.00
 -945.83   54.17
Pier Skew, UpSta & Num, DnSta & Num=  ,10821.73, 2 ,10673.52, 2 , 0 , 0 , 0 ,,
    4.00    4.00
 -947.80   52.20
    4.00    4.00
 -947.20   52.80
BR Coef=-1 , 0 , 0 ,, 0 ,,,0.8,0,1,0,
WSPro=,,,, 1 ,,,, 0 ,,,, 0 ,,,,-1 ,-1 ,-1 , 0 , 0 , 0 , 0 , 0
BC Design=,, 0 ,, 0 ,,,,,,

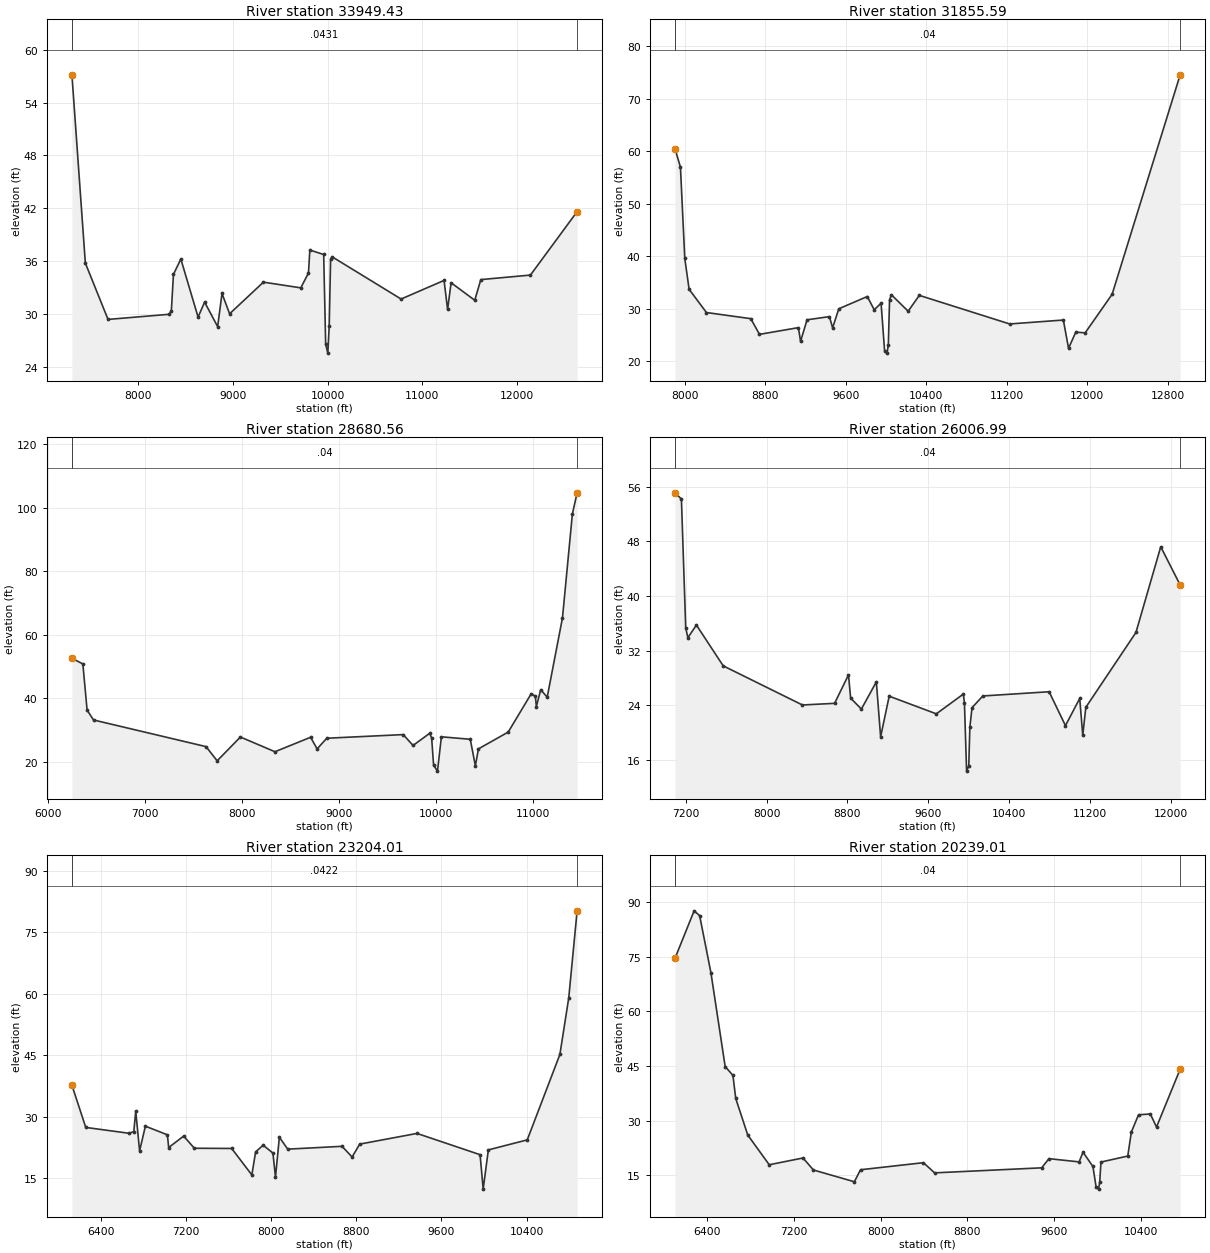
Type RM Length L Ch R = 1 ,33949.43,2093.842800,2093.842800,2093.842800
XS GIS Cut Line= 6
886322.930211507795396.318027596886011.776196311795188.882017465
884767.160135527794538.287258419884229.712291097794113.986328606
883220.818969098792916.514815578882739.944581976791700.185483448
#Sta/Elev= 30
7298.164 57.15527439.89935.789627679.68229.392338326.50829.974458348.81330.37179
8371.11734.502778449.18236.246558631.40729.655318700.35231.357068838.24228.57141
8884.20632.335668964.64230.031239321.89533.622549716.85832.974579797.94934.65765
9812.57137.265689958.78236.761589979.74526.5729310002.65 25.566110017.2728.67231
10031.8936.2017110048.2836.4988210776.8831.7055511230.8933.8183211268.3930.52461
11305.3633.55313 11555.3 31.568111619.4933.9128812143.7634.42533 12637.2 41.6284
#Mann= 3 , 0 , 0
7298.164  0.0431       07298.164  0.0431       0 12637.2  0.0431       0
#XS Ineff= 2 , 0
       09023.572        11135.17       0
Bank Sta=7298.164,12637.2
Exp/Cntr=0.3,0.1

Type RM Length L Ch R = 1 ,31855.59,3175.025300,3175.025300,3175.025300
XS GIS Cut Line= 4
886706.223462334795505.749101331886176.731394852794176.615952345
885042.105535962792598.945710459884631.479034649790999.663547451
#Sta/Elev= 30
7900.23360.487257954.86156.984317997.91839.613888040.97533.741848213.20429.31293
 8654.54 28.14188741.17725.156539128.16926.437989149.69823.830889214.28427.92904
9436.68128.530919468.43526.397289530.02330.02468 9813.4832.358989881.989 29.8412
9950.49831.076539985.77221.9761210010.4121.5850910022.7223.2241110035.0431.78126
10053.2632.69175 10219.829.5593810330.6632.5773711229.8427.1350311763.5727.88248
11815.1922.5018611887.4625.5862711980.3825.4411912248.8232.7857312925.4174.54499
#Mann= 3 , 0 , 0
7900.233    0.04       07900.233    0.04       012925.41    0.04       0
#XS Ineff= 2 , 0
       09020.137                       0
Bank Sta=7900.233,12925.41
Exp/Cntr=0.3,0.1

Type RM Length L Ch R = 1 ,28680.56,2673.572300,2673.572300,2673.572300
XS GIS Cut Line= 6
887643.491893053795597.610177316886170.614078237792555.838759616
886111.877884523792021.057012874886036.988518612791770.001132964
885849.250362444791307.632116245 885612.71377173790842.226131116
#Sta/Elev= 30
6250.76952.598426363.20650.853126407.03636.326936473.09933.22451 7631.8924.83989
7746.17520.374997985.52727.864178341.39223.237218708.37827.785778775.10324.13196
 8875.1927.483389661.78628.626139763.33125.209949934.666 29.03729954.71427.58377
9974.76219.0013810014.8617.1379910054.9627.93353 10352.427.1487510404.9418.81516
10436.5324.1414710742.9729.4135210977.6741.3533211021.9640.7849811033.0337.43842
11077.4342.7436911144.5340.3954311301.73 65.317711403.8798.0365211452.63104.6488
#Mann= 3 , 0 , 0
6250.769    0.04       06250.769    0.04       011452.63    0.04       0
#XS Ineff= 2 , 0
       07379.258                       0
Bank Sta=6250.769,11452.63
Exp/Cntr=0.3,0.1

Type RM Length L Ch R = 1 ,26006.99,2802.974800,2802.974800,2802.974800
XS GIS Cut Line= 6
 888117.45333813 795535.45250494887239.001476959793024.742117944
887060.936910505792567.709730713886951.931380929792227.612478435
886832.595074312791308.090390968886712.047815445790758.666298815
#Sta/Elev= 30
7093.70255.126847157.74854.216347200.12635.367087221.31533.89833 7306.07 35.7517
7570.931 29.77348354.91824.03729 8672.7524.280248810.47828.441948831.66725.04839
8937.61123.437729085.93327.41848 9128.3119.371699213.06625.32673 9679.2222.74003
9946.55725.634379957.28924.396699978.75314.3451210000.2215.1285110010.9520.76125
10032.4123.6461310139.7425.3603510794.9425.9781710956.8421.0122811097.8224.99539
11128.0319.5943711158.2323.6977211653.9134.6601211899.4347.2200112091.4341.62156
#Mann= 3 , 0 , 0
7093.702    0.04       07093.702    0.04       012091.43    0.04       0
#XS Ineff= 2 , 0
       08013.076                       0
Bank Sta=7093.702,12091.43
Exp/Cntr=0.3,0.1

Type RM Length L Ch R = 1 ,23204.01,2965.001100,2965.001100,2965.001100
XS GIS Cut Line= 6
890153.721502997794744.012041915888645.820032111792478.918881503
888481.254624517792176.662452051888271.000905787791661.960579798
887935.869192374791200.306866265887758.973369243 790679.09000969
#Sta/Elev= 30
6129.18137.657356259.262 27.36436665.94325.933396710.54426.344986728.66331.36564
6764.90221.625576819.25927.671897026.03925.555157038.09822.45818 7178.9225.24934
7279.288 22.27737629.96722.228757819.36315.765997854.85321.394217925.83123.02283
8017.33921.10401 8041.5515.232438077.866 24.9701 8156.5122.060738666.57322.75225
8761.18220.145828832.94823.289749370.86925.89931  9963.520.70679 9992.5712.30189
 10041.121.8792710406.5724.3218510713.2945.1785410796.3358.9754610875.1380.23222
#Mann= 3 , 0 , 0
6129.181  0.0422       06129.181  0.0422       010875.13  0.0422       0
#XS Ineff= 2 , 0
       07644.298                       0
Bank Sta=6129.181,10875.13
Exp/Cntr=0.3,0.1

Type RM Length L Ch R = 1 ,20239.01,570.875400,570.875400,570.875400
XS GIS Cut Line= 6
892178.110837489794393.082104168890886.612647561792448.360857003
  890549.6593485791997.906079191889980.795187384791326.314769698
889769.040177054790921.824157604889620.464157875790537.599023381
#Sta/Elev= 30
6109.37574.579086285.60887.665326336.44286.346246440.32170.632426571.23244.84951
6642.63842.440916668.43636.082976779.101 26.02376976.41717.862097287.35319.71986
7383.02516.420357759.65613.18384 7816.1216.484028394.77418.426498497.691 15.6298
9482.48117.013819549.60719.535239826.61818.648699862.90121.29814 9953.9817.38677
9982.63311.8280410005.1411.1589510016.39 13.070810027.6418.5986110274.31 20.2549
10307.4526.8560910373.2131.5902310481.7631.8228110538.75 28.222410756.18 44.1366
#Mann= 3 , 0 , 0
6109.375    0.04       06109.375    0.04       010756.18    0.04       0
#XS Ineff= 2 , 0
       07911.769                       0
Bank Sta=6109.375,10756.18
Exp/Cntr=0.3,0.1

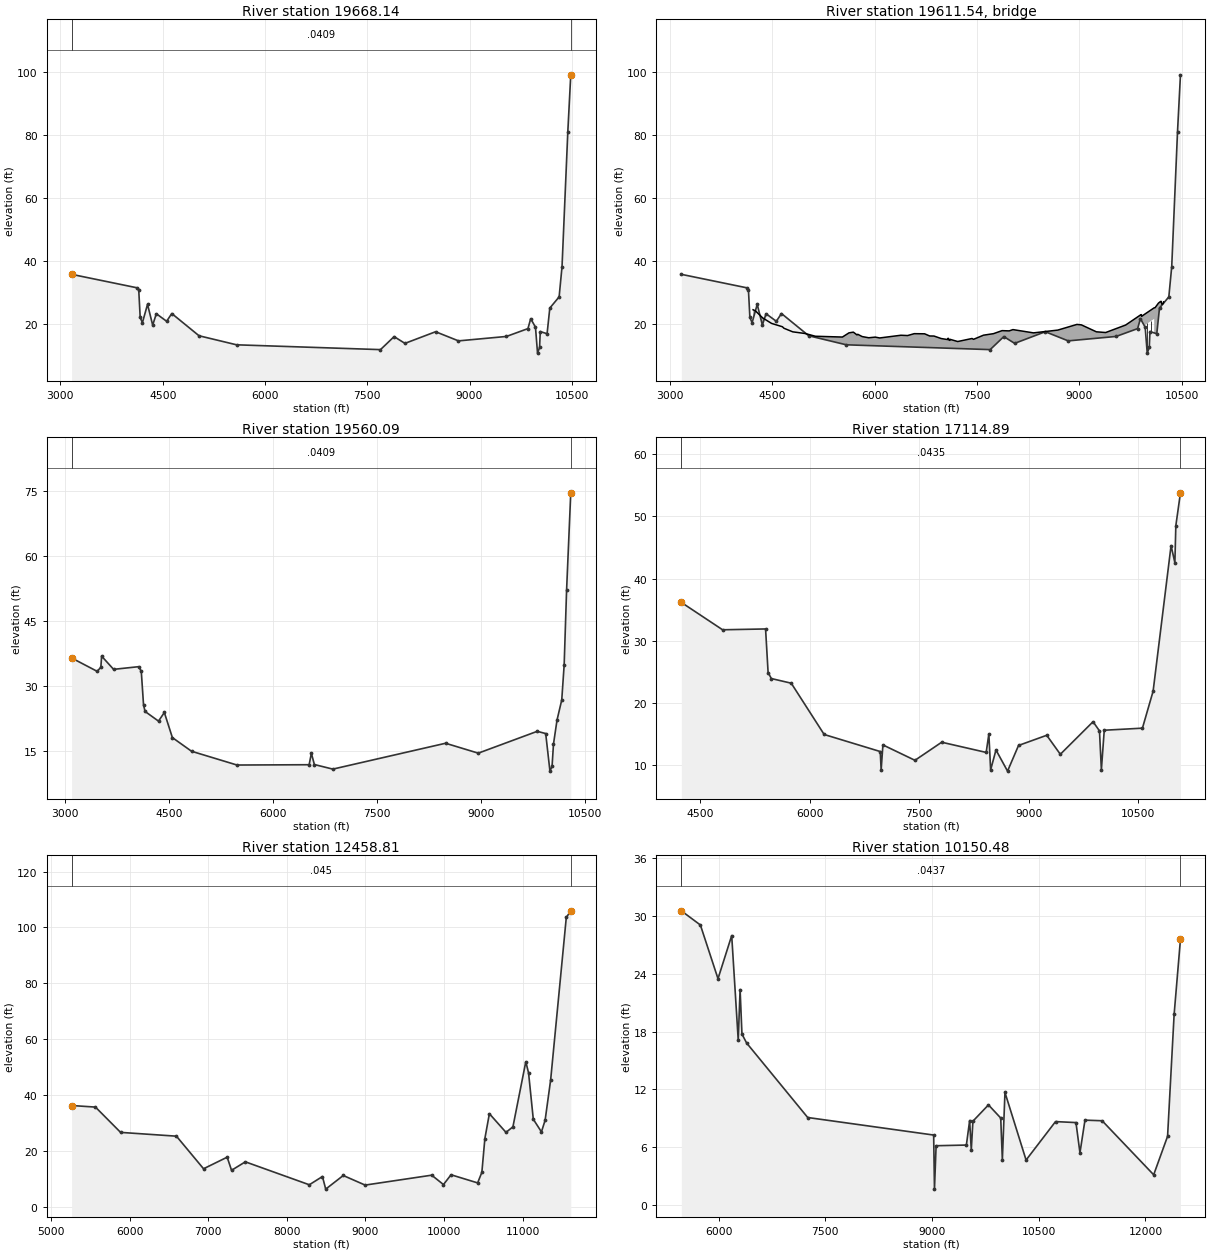
Type RM Length L Ch R = 1 ,19668.14,108.046600,108.046600,108.046600
XS GIS Cut Line= 6
896638.663055196793087.567033851 893183.98407083 791712.74679337
890343.615725441790793.616994832890018.126599266790782.818777376
889947.166884555790756.594534983 889874.66456735790554.513608306
#Sta/Elev= 30
3164.431  35.7414126.82631.462294148.36530.934684169.90322.08653 4202.2120.40559
4277.59426.224454352.978 19.65294406.82323.255034557.67820.864394633.28523.31749
5032.91916.274445583.76513.407197693.93711.882897893.63516.006088052.61613.86134
8502.09217.551838837.792 14.65389540.97116.058099856.24718.542739896.84221.68633
9966.88118.989079996.89710.7724210026.9112.5572310036.9217.6116810136.9716.91721
   1017725.0527310313.7228.6006110356.2238.2024710441.2180.9885810484.2298.96367
#Mann= 3 , 0 , 0
3164.431  0.0409       03164.431  0.0409       010484.22  0.0409       0
#XS Ineff= 2 , 0
       06684.223                       0
Bank Sta=3164.431,10484.22
Exp/Cntr=0.3,0.1

Type RM Length L Ch R = 3 ,19611.54,,,
BEGIN DESCRIPTION:
END DESCRIPTION:
Bridge Culvert--1,0,-1,-1, 0
Deck Dist Width WeirC Skew NumUp NumDn MinLoCord MaxHiCord MaxSubmerge Is_Ogee
39.588300,28.870000,2.6,0, 60, 60, , , 0.95, 0, 0,0,,
 4216.91 4251.80 4358.95 4487.52 4646.95 4669.67 4798.25 4980.40 5130.40 5526.85
 5623.28 5687.57 5741.14 5751.85 5816.55 5912.57 6009.01 6073.29 6385.04 6482.58
 6580.13 6731.87 6806.11 6869.42 6974.93 7069.89 7072.85 7080.44 7090.99 7101.54
 7104.20 7217.61 7427.89 7448.85 7595.53 7742.22 7867.95 7972.72 8027.36 8328.94
 8685.19 8965.60 9030.94 9250.97 9387.18 9680.54 9900.51 9910.54 9914.26 9948.31
 9948.3110099.2310099.2310111.2310161.4110191.5110201.5510211.5810231.6510237.04
   24.52   24.15   21.91   20.19   19.13   18.65   17.52   16.99   16.12   15.87
   17.20   17.42   16.54   16.74   16.02   15.64   15.85   15.58   16.44   16.34
   16.94   16.90   16.21   16.19   15.40   15.07   15.42   15.46   14.86   14.82
   15.15   14.45   15.41   15.14   16.46   16.94   17.90   17.82   18.23   17.19
   18.07   19.87   19.73   17.53   17.30   19.68   22.90   22.98   22.42   22.94
   22.94   25.14   25.14   25.15   26.62   27.13   27.17   26.27   26.47   27.01
 -975.48 -975.85 -978.09 -979.81 -980.87 -981.35 -982.48 -983.01 -983.88 -984.13
 -982.80 -982.58 -983.46 -983.26 -983.98 -984.36 -984.15 -984.42 -983.56 -983.66
 -983.06 -983.10 -983.79 -983.81 -984.60 -984.93 -984.58 -984.54 -985.14 -985.18
 -984.85 -985.55 -984.59 -984.86 -983.54 -983.06 -982.10 -982.18 -981.77 -982.81
 -981.93 -980.13 -980.27 -982.47 -982.70 -980.32 -977.10 -977.02 -977.58 -977.06
   19.44   21.64 -974.86 -974.85 -973.38 -972.87 -972.83 -973.73 -973.53 -972.99
 4216.91 4251.80 4358.95 4487.52 4646.95 4669.67 4798.25 4980.40 5130.40 5526.85
 5623.28 5687.57 5741.14 5751.85 5816.55 5912.57 6009.01 6073.29 6385.04 6482.58
 6580.13 6731.87 6806.11 6858.87 6869.42 6974.93 7069.89 7072.85 7080.44 7090.99
 7101.54 7104.20 7217.61 7427.89 7448.85 7522.19 7595.53 7742.22 7867.95 7972.72
 8027.36 8328.94 8685.19 8965.60 9030.94 9250.97 9387.18 9680.54 9900.51 9910.54
 9914.26 9953.41 9953.4110104.3310104.3310191.5110201.5510211.5810231.6510237.04
   24.52   24.15   21.91   20.19   19.13   18.65   17.52   16.99   16.12   15.87
   17.20   17.42   16.54   16.74   16.02   15.64   15.85   15.58   16.44   16.34
   16.94   16.90   16.21   15.95   16.19   15.40   15.07   15.42   15.46   14.86
   14.82   15.15   14.45   15.41   15.14   15.58   16.46   16.94   17.90   17.82
   18.23   17.19   18.07   19.87   19.73   17.53   17.30   19.68   22.90   22.98
   22.42   23.02   23.02   25.14   25.14   27.13   27.17   26.27   26.47   27.01
 -975.48 -975.85 -978.09 -979.81 -980.87 -981.35 -982.48 -983.01 -983.88 -984.13
 -982.80 -982.58 -983.46 -983.26 -983.98 -984.36 -984.15 -984.42 -983.56 -983.66
 -983.06 -983.10 -983.79 -984.05 -983.81 -984.60 -984.93 -984.58 -984.54 -985.14
 -985.18 -984.85 -985.55 -984.59 -984.86 -984.42 -983.54 -983.06 -982.10 -982.18
 -981.77 -982.81 -981.93 -980.13 -980.27 -982.47 -982.70 -980.32 -977.10 -977.02
 -977.58 -976.98   19.52   21.64 -974.86 -972.87 -972.83 -973.73 -973.53 -972.99
Pier Skew, UpSta & Num, DnSta & Num=  ,9997.95, 2 ,10003.05, 2 , 0 , 0 , 0 ,,
    4.00    4.00
 -976.30   23.70
    4.00    4.00
 -976.23   23.77
Pier Skew, UpSta & Num, DnSta & Num=  ,10049.59, 2 ,10054.69, 2 , 0 , 0 , 0 ,,
    4.00    4.00
 -975.52   24.48
    4.00    4.00
 -975.44   24.56
BR Coef=-1 , 0 , 0 ,, 0 ,,,0.8,0,1,0,
WSPro=,,,, 1 ,,,, 0 ,,,, 0 ,,,,-1 ,-1 ,-1 , 0 , 0 , 0 , 0 , 0
BC Design=,, 0 ,, 0 ,,,,,,

Type RM Length L Ch R = 1 ,19560.09,2445.198200,2445.198200,2445.198200
XS GIS Cut Line= 6
896775.600905757792989.754283451895609.983867245792515.312725879
893383.045114449791662.981532465890565.750484536790758.137137476
890112.225351383790668.666192841890044.350841659790552.971005812
#Sta/Elev= 30
3095.98436.452063463.719 33.37263517.70234.302693528.49936.877043701.24533.82736
4063.50934.44317 4100.7233.36524 4133.1125.646924154.70424.112164349.04321.87436
4433.34823.867414549.07718.073284825.833 14.91565481.16411.737476521.62711.80862
6553.98814.450736597.13711.853116863.62210.79441 8489.5716.766088961.177 14.4778
9811.42319.519299933.63219.004579994.851 10.330510025.4611.4477310045.8716.56677
10096.8822.1122110165.1826.7705410199.9734.8704810234.7552.0320310295.0774.57814
#Mann= 3 , 0 , 0
3095.984  0.0409       03095.984  0.0409       010295.07  0.0409       0
#XS Ineff= 2 , 0
       06640.722                       0
Bank Sta=3095.984,10295.07
Exp/Cntr=0.3,0.1

Type RM Length L Ch R = 1 ,17114.89,4656.080400,4656.080400,4656.080400
XS GIS Cut Line= 4
897055.997456905793028.879383611895759.957275558792377.315859238
892736.246226426 790268.34092581891436.588706559 789173.82724851
#Sta/Elev= 30
4240.20336.148544805.426 31.73465394.15631.868575428.80224.836175473.32923.87181
 5745.6223.121916196.72814.852246964.83212.102846977.0249.1370667001.408  13.171
7440.32410.688857806.08813.606858415.69411.96156 8452.2714.930958476.6549.147059
8549.80712.354758708.3048.9459248858.784 13.08619244.75814.725159431.27611.66294
 9879.3116.911599967.29915.436859993.4469.17340410032.6715.5391110555.6215.87248
10702.0921.8395210947.8345.3049411000.1242.54893 11013.248.5271411076.49 53.8154
#Mann= 3 , 0 , 0
4240.203  0.0435       04240.203  0.0435       011076.49  0.0435       0
#XS Ineff= 2 , 0
       07730.356                       0
Bank Sta=4240.203,11076.49
Exp/Cntr=0.3,0.1

Type RM Length L Ch R = 1 ,12458.81,2308.328400,2308.328400,2308.328400
XS GIS Cut Line= 6
898053.687510992792344.190130806 894899.44067087789072.160370255
894448.051781981 788502.71592581 894399.44067087788398.549259143
894303.504714035788259.006049201893626.385077097787847.535066036
#Sta/Elev= 30
5262.929 36.27915566.08235.715045885.66826.665686596.03725.309976940.83913.65206
7241.145 17.79357296.85613.100647472.40816.132028285.7267.9224218452.85910.87041
8494.6436.3646968717.487 11.24238996.0427.8074519842.46511.356779992.0347.994916
10088.6211.5020310426.688.592404 10480.512.3880710518.7824.4707210576.0833.34744
 10787.2 26.6762 10875.528.6466111039.3351.9534211074.4347.9368211134.5631.37213
11238.25 26.842711285.0631.0280111355.2745.43445 11554.2103.545911611.08105.9318
#Mann= 3 , 0 , 0
5262.929   0.045       05262.929   0.045       011611.08   0.045       0
#XS Ineff= 2 , 0
       08643.035                       0
Bank Sta=5262.929,11611.08
Exp/Cntr=0.3,0.1

Type RM Length L Ch R = 1 ,10150.48,3634.196100,3634.196100,3634.196100
XS GIS Cut Line= 3
899488.274516868790505.310423274898586.540451055789440.821144898
893697.545774769786668.127404875
#Sta/Elev= 30
5477.28630.516995745.36129.046395992.89923.475076185.399 27.95116277.13917.11076
 6303.3522.353166329.56217.734576395.14916.807587253.5189.0810839023.9397.260764
9035.4351.6522089058.4286.1534789483.7896.2231859529.7748.7682439552.7665.708837
9575.7598.6983489794.18810.389329966.6319.0270739989.6244.69111510026.1611.68111
10323.014.66920410736.888.65663911024.29 8.5545311080.255.41838111150.748.806696
11392.178.74469712116.433.13966412311.867.13095212403.8319.7683112492.8827.55749
#Mann= 3 , 0 , 0
5477.286  0.0437       05477.286  0.0437       012492.88  0.0437       0
#XS Ineff= 2 , 0
       0 7987.78        11178.42       0
Bank Sta=5477.286,12492.88
Exp/Cntr=0.3,0.1

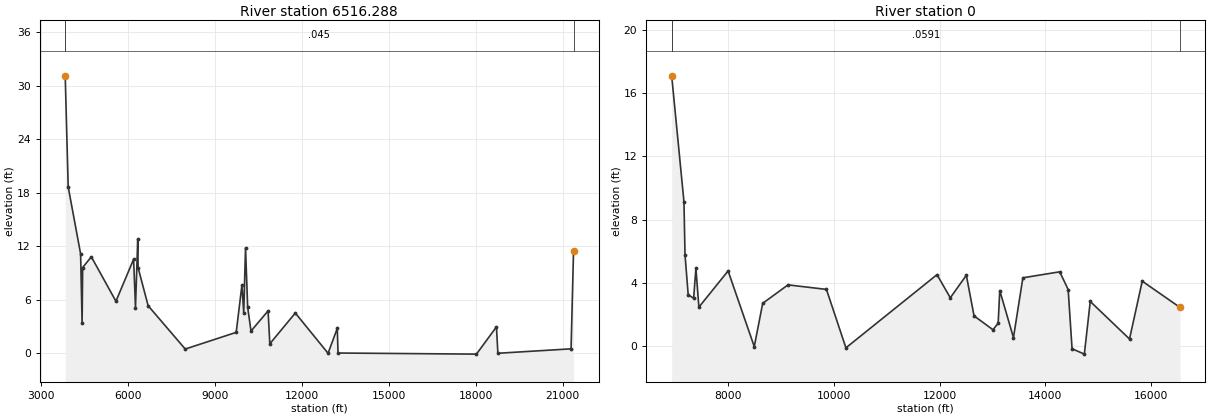
Type RM Length L Ch R = 1 ,6516.288,6516.287700,6516.287700,6516.287700
XS GIS Cut Line= 4
902264.549628615 789837.78724128900146.227973074788091.906472757
 895652.65978536784837.943302363890275.405481488777335.635718405
#Sta/Elev= 30
3851.31131.086973954.39718.642594382.03311.145084433.8683.3514724453.1719.609559
 4751.9110.806875600.1495.8270466209.20710.536996274.0015.1180786351.75312.78821
6364.7129.5816446710.4525.3238727989.2030.4743299746.2662.3427019943.8117.649829
10005.544.52494610067.2811.8195510141.36 5.1367710256.852.49288310845.114.750994
10904.76 1.0620311783.454.51158212912.82       0 13230.7 2.7917613256.130.028189
18028.16-0.09587   187182.96222318766.28       0 21289.40.49645321374.74   11.42
#Mann= 3 , 0 , 0
3851.311   0.045       03851.311   0.045       021374.74   0.045       0
#XS Ineff= 2 , 0
       08751.543        11985.59       0
Bank Sta=3851.311,21374.74
Exp/Cntr=0.3,0.1

Type RM Length L Ch R = 1 ,       0,0.000000,0.000000,0.000000
XS GIS Cut Line= 6
903306.357231385786168.561606899 903178.45423715785978.862783989
901490.180153002 785004.04099253898905.055340582782893.194464678
897387.430522682780961.241496861896736.280584825779492.183710231
#Sta/Elev= 30
6932.72417.088767164.9739.1386217185.0045.7854517245.0843.2525047348.1973.032561
7391.173 4.924687447.3942.4686317999.9014.7583918494.877-0.024338654.4712.711237
9133.2533.8776999860.014 3.5907510228.44-0.1028111951.334.52279412202.843.060509
 12506.34.48424912651.921.91805613009.331.04357913108.041.44781913138.573.515093
13397.440.54424313575.574.32354514272.524.70293514432.243.58230114505.96-0.15896
 14738.2-0.4996914849.962.82884915592.770.45680515833.41 4.1115116547.48 2.45253
#Mann= 3 , 0 , 0
6932.724  0.0591       06932.724  0.0591       016547.48  0.0591       0
#XS Ineff= 2 , 0
       09714.236        13170.55       0
Bank Sta=6932.724,16547.48
Exp/Cntr=0.3,0.1